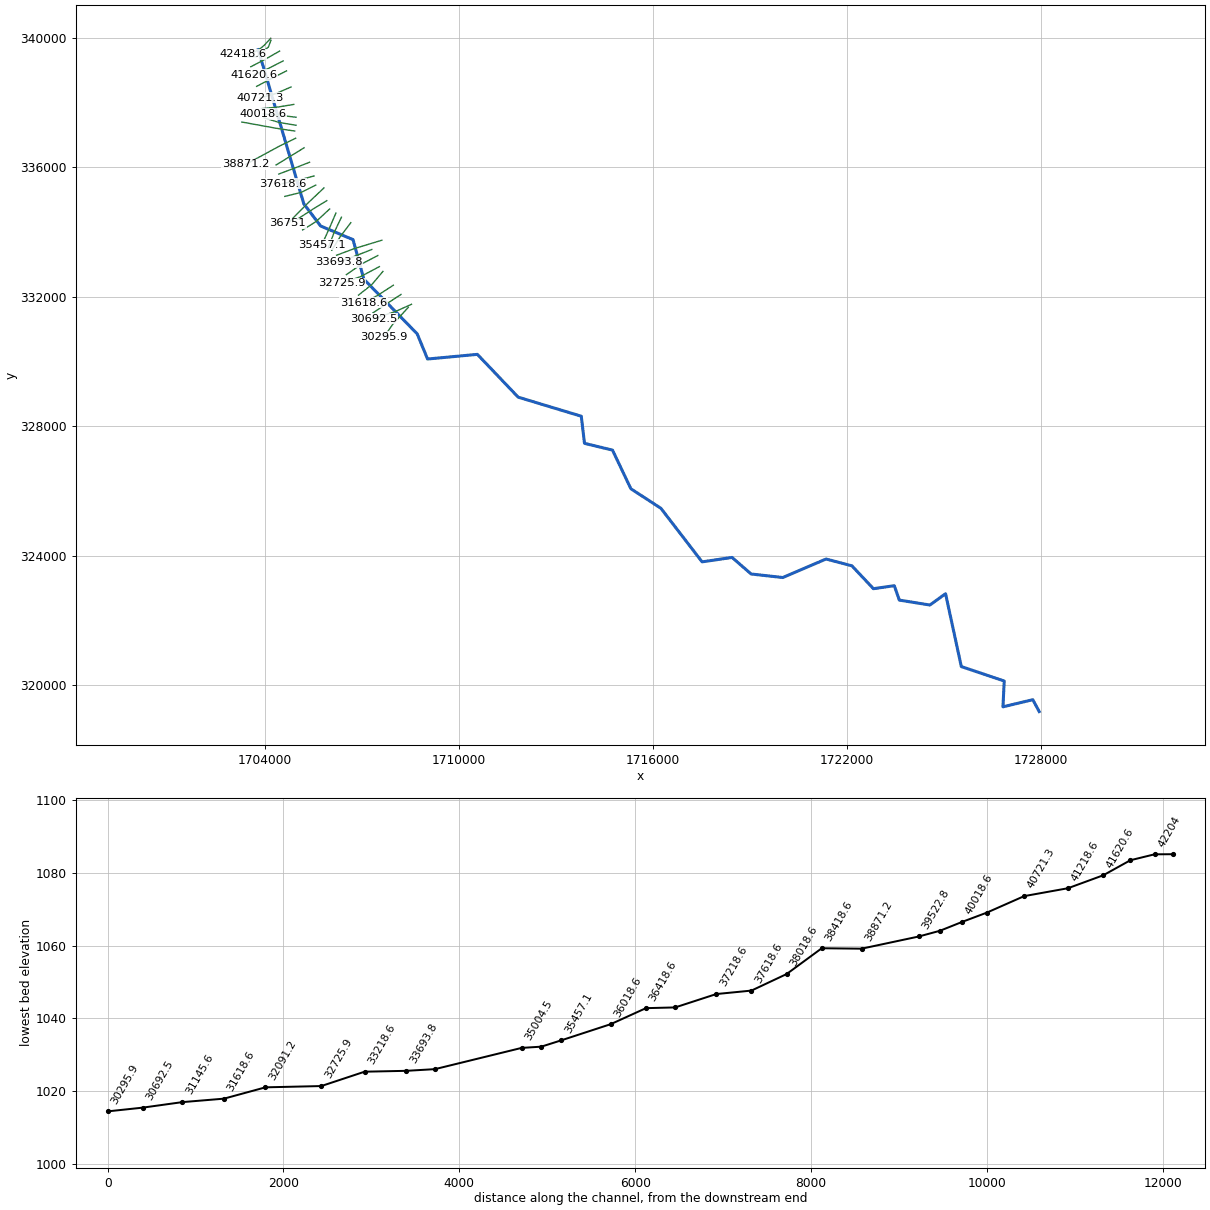
--- JonesCr.prj (project) ---

Proj Title=JonesCr
Current Plan=p01
Geom File=g01
Flow File=f01
Plan File=p01
DSS Export Rating Curves=0
DSS Export Rating Curve Sorted=0
DSS Export Volume Flow Curves=0
DXF OffsetX=0
DXF OffsetY=0
DXF ScaleX=0
DXF ScaleY=0

--- JonesCr.p01 (plan) ---

Plan Title=Floodplain
Program Version=4.00
Geom File=g01
Flow File=f01
K Sum by GR=0
Std Step Tol=0.01
Critical Tol=0.01
Num of Std Step Trials=20
Max Error Tol=0.3
Flow Tol Ratio=0.001
Split Flow NTrial=30
Split Flow Tol=0.02
Split Flow Ratio=0.02
Log Output Level=0
Friction Slope Method=1
Unsteady Friction Slope Method=2
Unsteady Bridges Friction Slope Method=1
Global Log Level=0
CheckData=False
Run HTab=0
Run UNet=0
Run PostProcess=0
UNET Theta=0
UNET Theta Warmup=0
UNET ZTol=0
UNET ZSATol=0
UNET MxIter=0
UNET MaxInSteps=0
UNET DtIC=0
UNET DtMin=0
UNET MaxCRTS=0
UNET WFStab=0
UNET SFStab=0
UNET WFX=0
UNET SFX=0
UNET DSS MLevel=0
UNET DZMax Abort=0
UNET Convert EG Bridges=0
UNET Use Existing IB Tables=0
UNET Froude Limit=0
UNET Froude Power=0
Write IC File=0
Echo Input=False
Echo Output=False
Write Detailed=0

--- JonesCr.f01 (steady flow) ---

Flow Title=NFF Regression Equation
Program Version=4.00
Number of Profiles=1
Profile Names=P100yr
River Rch & RM=JonesCr,Main      ,42418.6
709.0545
River Rch & RM=JonesCr,Main      ,42204
709.0545
River Rch & RM=JonesCr,Main      ,41928.5
808.5590
River Rch & RM=JonesCr,Main      ,38871.2
889.1939
River Rch & RM=JonesCr,Main      ,38418.6
1099.486
River Rch & RM=JonesCr,Main      ,38018.6
1128.186
River Rch & RM=JonesCr,Main      ,36751
1235.376
River Rch & RM=JonesCr,Main      ,34018.6
1276.502
River Rch & RM=JonesCr,Main      ,33693.8
1498.817
River Rch & RM=JonesCr,Main      ,30295.9
1575.577
River Rch & RM=JonesCr,Main      ,26818.6
1649.861
River Rch & RM=JonesCr,Main      ,26530.8
1933.356
River Rch & RM=JonesCr,Main      ,22818.6
2142.283
River Rch & RM=JonesCr,Main      ,20456
2266.281
River Rch & RM=JonesCr,Main      ,14018.6
2442.188
River Rch & RM=JonesCr,Main      ,9859.9
2710.083
River Rch & RM=JonesCr,Main      ,346
2957.697
River Rch & RM=JonesCr,Main      ,19.5
2960.968
Boundary for River Rch & Prof#=JonesCr,Main      ,1
Up Type=0
Dn Type=3
Dn Slope=0.00432

--- JonesCr.g01 (geometry) ---

Geom Title=USGS 3m DEM
Program Version=4.00

River Reach=JonesCr     ,Main
Reach XY= 30
     1703804.769      339635.051     1705212.027      334874.476
     1705731.509      334189.897     1706733.327      333768.069
     1707066.807      332548.837     1708715.608      330858.274
     1709037.129      330080.613     1710575.968      330224.186
     1711836.381      328902.266     1713786.714      328313.971
     1713886.560      327475.282     1714751.370      327267.434
     1715319.771      326072.632     1716246.557      325470.565
     1717519.847      323815.320     1718446.420      323951.623
     1719035.003      323440.753     1720013.915      323331.201
     1721352.431      323903.024     1722150.853      323691.913
     1722814.920      322986.026     1723459.567      323079.031
     1723615.849      322633.909     1724560.512      322481.671
     1725043.956      322831.566     1725531.341      320580.684
     1726857.089      320134.275     1726817.986      319337.340
     1727739.668      319557.939     1727939.192      319190.529

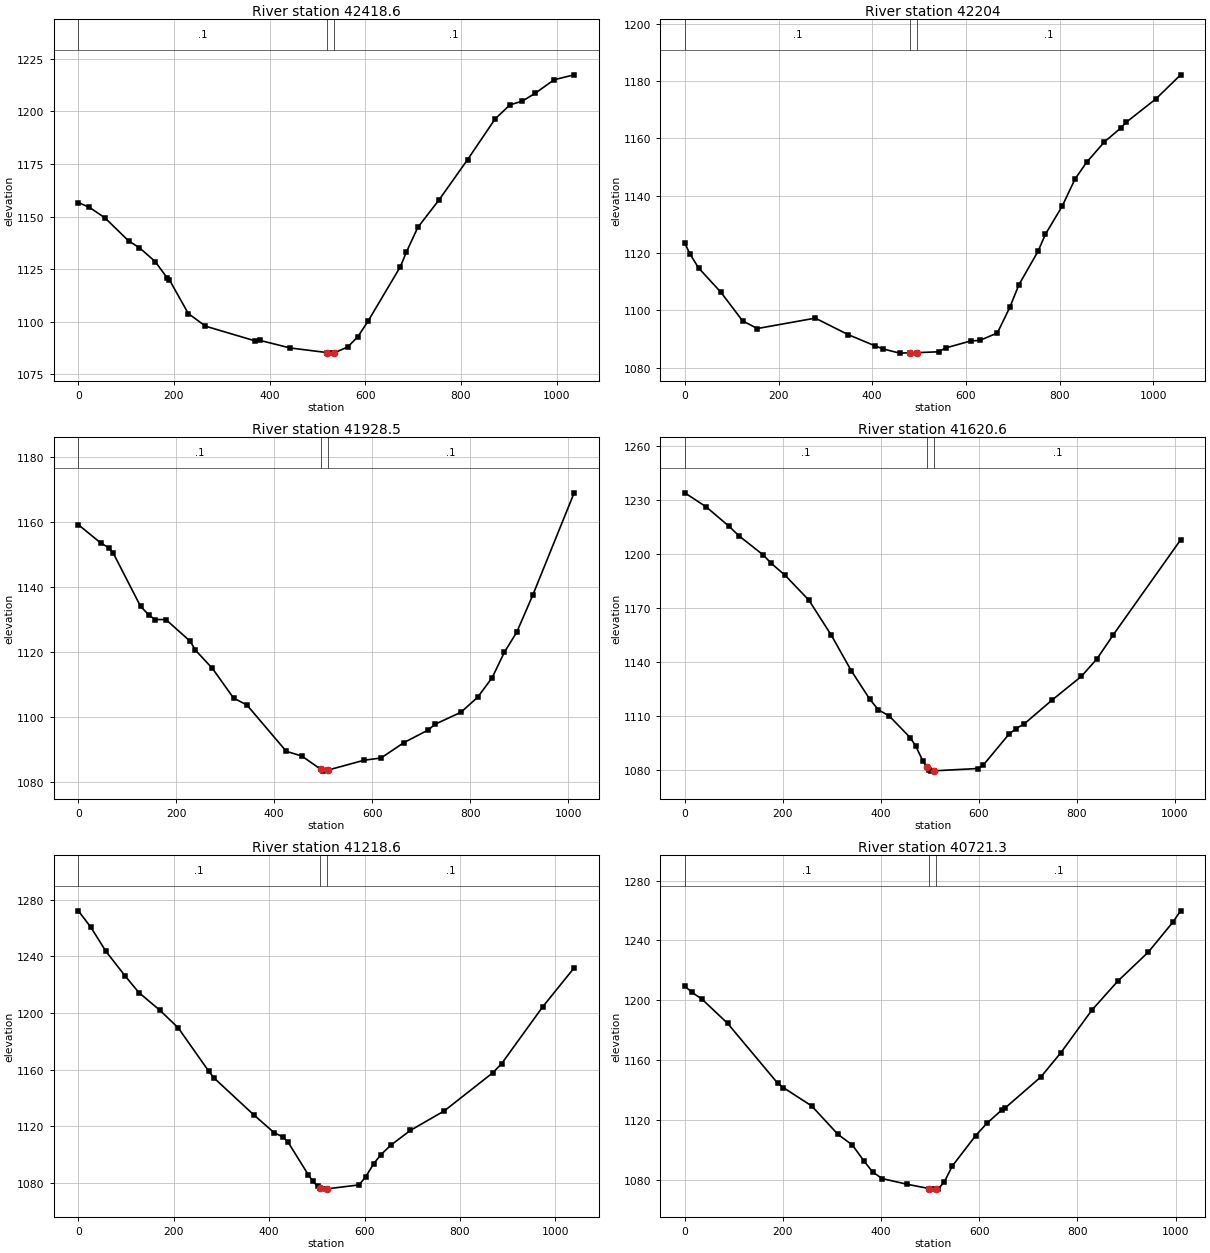
Type RM Length L Ch R = 1 ,42418.6,214.886,214.631,170.853
XS GIS Cut Line= 5
     1704190.723      339988.780     1703984.148      339766.220
     1703809.241      339626.107     1703686.200      339565.940
     1703322.575      339486.949
#Sta/Elev= 30
       0 1156.63    23.2 1154.37    55.6 1149.37   105.5 1138.34   127.6 1135.21
   160.7 1128.59   185.2 1121.01   190.2 1120.01   229.9 1103.90   265.9 1097.88
   368.5 1090.97   379.3 1091.16   442.5 1087.54   520.3 1085.33   527.4 1085.07
   535.3 1085.20   563.5 1088.03   584.5 1092.88   605.7 1100.23   673.4 1126.15
   686.1 1133.18   709.9 1144.84   754.5 1157.97   814.0 1177.07   871.5 1196.39
   902.4 1203.05   928.6 1204.89   955.1 1208.56   994.9 1215.02  1036.8 1217.36
#Mann= 3 , 0 , 0
       0     0.1       0   520.3   0.045       0   535.3     0.1       0
Bank Sta=   520.3,   535.3
Exp/Cntr=0.3,0.1

Type RM Length L Ch R = 1 ,42204,269.22,275.481,271.678
XS GIS Cut Line= 4
     1704196.686      339927.003     1704116.656      339716.015
     1703745.610      339417.723     1703389.114      339417.723
#Sta/Elev= 30
       0 1123.48    10.5 1119.81    29.3 1114.81    76.7 1106.36   123.3 1096.32
   154.7 1093.63   278.5 1097.26   348.8 1091.49   404.9 1087.66   423.3 1086.49
   458.7 1085.04   481.2 1085.17   496.2 1085.20   541.5 1085.51   556.4 1086.83
   610.4 1089.30   629.7 1089.48   667.0 1092.07   693.7 1101.02   712.9 1108.88
   753.8 1120.58   769.6 1126.53   805.3 1136.32   833.0 1145.88   857.7 1151.71
   895.3 1158.76   929.9 1163.58   942.4 1165.70  1005.8 1173.88  1058.2 1182.23
#Mann= 3 , 0 , 0
       0     0.1       0   481.2   0.045       0   496.2     0.1       0
Bank Sta=   481.2,   496.2
Exp/Cntr=0.3,0.1

Type RM Length L Ch R = 1 ,41928.5,308.927,307.923,306.809
XS GIS Cut Line= 3
     1704463.559      339592.260     1704029.351      339344.969
     1703574.371      339108.612
#Sta/Elev= 30
       0 1159.17    46.9 1153.40    62.5 1152.11    71.6 1150.32   127.2 1134.02
   144.7 1131.33   156.5 1130.01   178.8 1130.00   228.3 1123.34   239.1 1120.60
   273.9 1114.96   316.9 1105.88   344.2 1103.74   424.6 1089.50   456.3 1088.05
   494.5 1084.03   499.7 1083.41   509.5 1083.72   583.7 1086.77   618.1 1087.45
   665.0 1092.20   714.9 1096.09   728.0 1097.79   781.2 1101.50   815.7 1106.18
   845.1 1112.18   870.0 1119.99   895.0 1126.07   927.6 1137.40  1012.4 1168.96
#Mann= 3 , 0 , 0
       0     0.1       0   494.5   0.045       0   509.5     0.1       0
Bank Sta=   494.5,   509.5
Exp/Cntr=0.3,0.1

Type RM Length L Ch R = 1 ,41620.6,383.637,401.965,390.774
XS GIS Cut Line= 3
     1704572.285      339287.248     1704128.426      339061.291
     1703659.091      338852.484
#Sta/Elev= 30
       0 1233.93    43.5 1226.16    89.6 1215.48   111.2 1209.89   160.1 1199.40
   176.3 1194.77   204.9 1188.04   253.3 1174.26   299.3 1154.68   339.6 1135.13
   377.1 1119.40   394.5 1113.49   417.6 1109.82   460.0 1097.89   470.9 1093.39
   485.7 1085.05   494.2 1081.55   497.6 1080.14   501.5 1079.29   509.2 1079.47
   598.3 1080.75   608.5 1082.45   661.0 1099.66   675.7 1102.92   692.5 1105.49
   748.9 1118.66   809.5 1132.00   841.3 1141.76   874.4 1155.05  1011.8 1207.81
#Mann= 3 , 0 , 0
       0     0.1       0   494.2   0.045       0   509.2     0.1       0
Bank Sta=   494.2,   509.2
Exp/Cntr=0.3,0.1

Type RM Length L Ch R = 1 ,41218.6,499.73,497.339,492.156
XS GIS Cut Line= 3
     1704676.864      338981.197     1704219.050      338747.350
     1703754.150      338502.767
#Sta/Elev= 30
       0 1272.19    26.3 1260.58    57.8 1243.61    97.5 1226.48   126.8 1214.52
   171.1 1201.95   209.3 1189.63   273.5 1158.89   284.7 1154.12   367.3 1128.30
   410.2 1115.66   429.4 1112.42   439.6 1108.88   482.0 1085.95   491.7 1081.22
   501.4 1077.83   506.6 1076.77   518.2 1075.73   521.6 1075.95   588.5 1078.70
   602.6 1084.48   619.3 1093.79   634.5 1100.09   654.6 1106.63   696.0 1117.16
   767.5 1131.04   868.7 1157.83   887.4 1164.33   973.4 1204.40  1039.4 1231.94
#Mann= 3 , 0 , 0
       0     0.1       0   506.6   0.045       0   521.6     0.1       0
Bank Sta=   506.6,   521.6
Exp/Cntr=0.3,0.1

Type RM Length L Ch R = 1 ,40721.3,429.945,424.933,422.418
XS GIS Cut Line= 3
     1704817.137      338483.852     1704359.821      338285.331
     1703867.068      338147.867
#Sta/Elev= 30
       0 1209.37    14.9 1205.25    35.3 1200.66    87.1 1184.56   189.4 1144.39
   200.6 1141.55   258.5 1129.25   312.1 1110.19   341.4 1103.09   365.4 1092.24
   382.9 1084.96   402.1 1080.63   452.6 1076.84   497.1 1073.99   504.1 1073.57
   512.1 1073.72   516.5 1073.80   528.8 1078.45   544.8 1088.97   592.5 1109.39
   615.1 1117.52   646.3 1126.73   653.2 1128.07   725.3 1148.64   765.8 1164.76
   829.2 1193.34   881.8 1212.70   944.4 1232.27   994.0 1252.17  1010.1 1259.86
#Mann= 3 , 0 , 0
       0     0.1       0   497.1   0.045       0   512.1     0.1       0
Bank Sta=   497.1,   512.1
Exp/Cntr=0.3,0.1

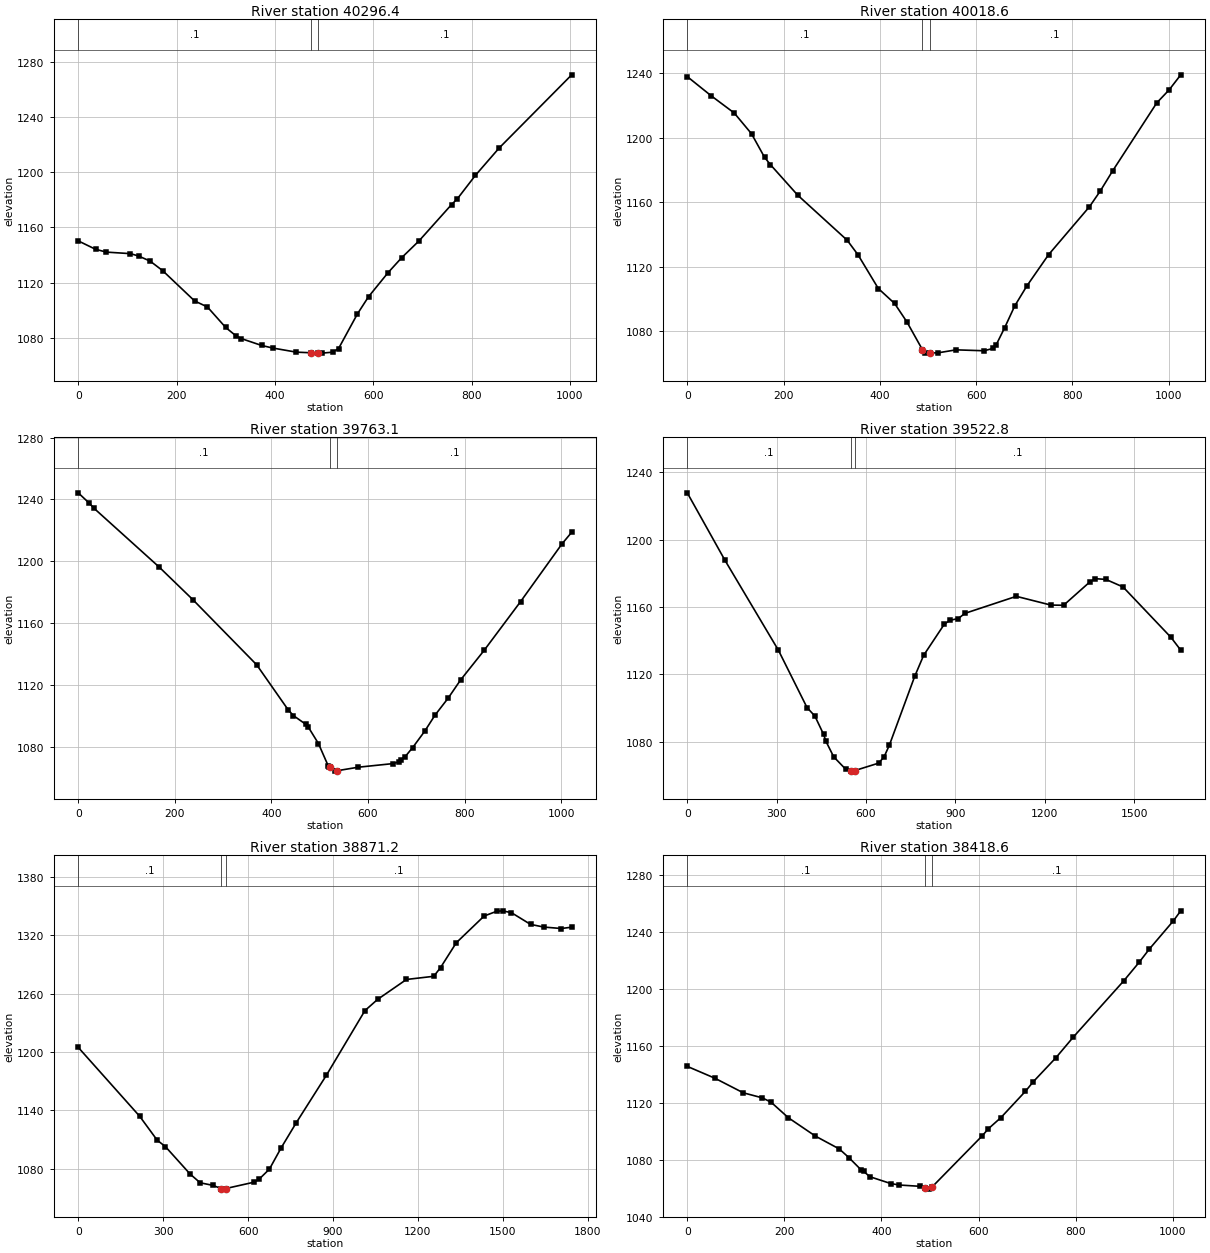
Type RM Length L Ch R = 1 ,40296.4,284.421,277.729,272.027
XS GIS Cut Line= 3
     1704900.753      337944.892     1704403.734      337863.052
     1703906.337      337814.063
#Sta/Elev= 30
       0 1150.26    35.3 1144.16    57.3 1142.12   106.3 1141.01   122.9 1139.28
   146.2 1135.62   171.8 1128.69   236.6 1106.82   262.8 1102.41   299.9 1087.60
   320.8 1081.55   331.7 1079.55   373.2 1074.56   396.0 1072.70   443.7 1069.74
   472.8 1069.31   487.8 1069.13   495.9 1069.04   517.4 1069.73   529.4 1072.34
   567.7 1097.37   590.4 1109.87   630.3 1127.35   657.9 1138.13   692.9 1150.19
   759.3 1176.56   771.2 1180.78   807.8 1197.70   856.0 1217.44  1003.5 1270.38
#Mann= 3 , 0 , 0
       0     0.1       0   472.8   0.045       0   487.8     0.1       0
Bank Sta=   472.8,   487.8
Exp/Cntr=0.3,0.1

Type RM Length L Ch R = 1 ,40018.6,256.422,255.558,250.852
XS GIS Cut Line= 3
     1704973.714      337548.607     1704481.363      337608.319
     1703953.713      337649.825
#Sta/Elev= 30
       0 1237.74    49.7 1225.86    97.6 1215.20   133.5 1202.35   160.5 1187.79
   172.6 1183.27   229.5 1164.31   332.2 1136.43   354.7 1127.41   396.9 1106.53
   430.8 1097.25   456.4 1085.80   488.5 1068.67   493.4 1066.52   503.5 1066.60
   521.7 1066.74   558.4 1068.55   616.8 1067.98   635.2 1069.45   641.8 1071.68
   659.1 1082.07   680.3 1095.73   705.4 1108.07   750.6 1127.47   835.6 1157.19
   858.0 1166.88   883.7 1179.36   975.5 1221.52  1001.2 1229.57  1025.2 1238.84
#Mann= 3 , 0 , 0
       0     0.1       0   488.5   0.045       0   503.5     0.1       0
Bank Sta=   488.5,   503.5
Exp/Cntr=0.3,0.1

Type RM Length L Ch R = 1 ,39763.1,220.067,240.237,217.445
XS GIS Cut Line= 3
     1704973.418      337301.526     1704458.611      337384.954
     1703980.038      337530.127
#Sta/Elev= 30
       0 1244.27    22.0 1237.83    33.1 1234.15   167.7 1196.17   237.5 1175.04
   369.5 1132.89   434.6 1103.78   445.5 1100.02   470.7 1094.47   476.6 1092.44
   497.3 1081.92   518.0 1067.16   518.8 1066.73   520.6 1066.45   531.1 1064.06
   535.6 1064.30   579.6 1066.59   651.5 1068.93   663.6 1070.06   667.6 1071.40
   676.3 1073.23   692.4 1079.33   717.2 1089.85   738.6 1100.29   765.7 1111.26
   791.7 1123.14   840.2 1142.21   915.7 1173.80  1001.9 1211.37  1021.6 1218.73
#Mann= 3 , 0 , 0
       0     0.1       0   520.6   0.045       0   535.6     0.1       0
Bank Sta=   520.6,   535.6
Exp/Cntr=0.3,0.1

Type RM Length L Ch R = 1 ,39522.8,633.522,651.619,664.757
XS GIS Cut Line= 3
     1704930.098      337122.564     1704351.546      337209.602
     1703297.179      337400.926
#Sta/Elev= 30
       0 1227.75   126.6 1187.67   306.0 1134.27   402.0 1100.25   428.5 1095.16
   457.6 1084.33   465.5 1080.20   491.6 1070.98   532.0 1063.59     548 1062.65
   556.4 1062.49     563 1062.85   642.4 1067.24   660.7 1070.96   678.6 1077.97
   763.5 1118.76   793.4 1131.22   862.8 1149.71   881.4 1152.03   909.8 1153.10
   932.0 1156.17  1104.6 1166.29  1220.5 1161.10  1263.3 1160.98  1350.5 1174.69
  1369.9 1176.77  1405.2 1176.34  1463.0 1171.84  1623.9 1141.90  1656.6 1134.32
#Mann= 3 , 0 , 0
       0     0.1       0     548   0.045       0     563     0.1       0
Bank Sta=     548,     563
Exp/Cntr=0.3,0.1

Type RM Length L Ch R = 1 ,38871.2,450.412,452.586,454.694
XS GIS Cut Line= 3
     1704959.338      336900.107     1704465.877      336660.337
     1703415.372      336091.711
#Sta/Elev= 30
       0 1204.81   217.2 1133.97   279.2 1109.34   307.7 1102.93   395.3 1074.62
   430.9 1065.65   474.5 1063.09   505.3 1059.73   510.7 1059.14   520.3 1059.69
   620.2 1066.21   638.3 1069.17   675.3 1079.65   716.8 1101.53   769.8 1127.15
   876.5 1176.06  1012.8 1242.57  1057.8 1254.13  1159.5 1274.56  1255.9 1277.82
  1279.8 1286.72  1335.6 1312.31  1434.0 1339.77  1478.0 1344.59  1499.0 1345.09
  1530.5 1343.16  1597.8 1331.17  1644.2 1328.43  1706.1 1326.92  1743.2 1328.27
#Mann= 3 , 0 , 0
       0     0.1       0   505.3   0.045       0   520.3     0.1       0
Bank Sta=   505.3,   520.3
Exp/Cntr=0.3,0.1

Type RM Length L Ch R = 1 ,38418.6,404.032,400,395.79
XS GIS Cut Line= 3
     1705222.108      336605.874     1704798.621      336345.431
     1704355.640      336074.807
#Sta/Elev= 30
       0 1145.56    56.8 1137.25   115.4 1126.97   154.4 1123.45   172.5 1120.40
   208.4 1109.40   263.9 1096.54   313.0 1087.52   332.7 1081.48   358.8 1072.53
   363.5 1071.67   376.1 1067.98   419.2 1063.17   437.0 1062.14   479.7 1061.23
   489.7 1060.08   496.9 1059.26   504.7 1060.95   607.9 1096.88   620.0 1101.69
   646.0 1109.56   696.4 1128.03   712.9 1134.87   759.1 1151.59   795.1 1166.18
   898.9 1205.68   930.6 1218.71   951.4 1227.95  1001.1 1247.86  1016.3 1254.92
#Mann= 3 , 0 , 0
       0     0.1       0   489.7   0.045       0   504.7     0.1       0
Bank Sta=   489.7,   504.7
Exp/Cntr=0.3,0.1

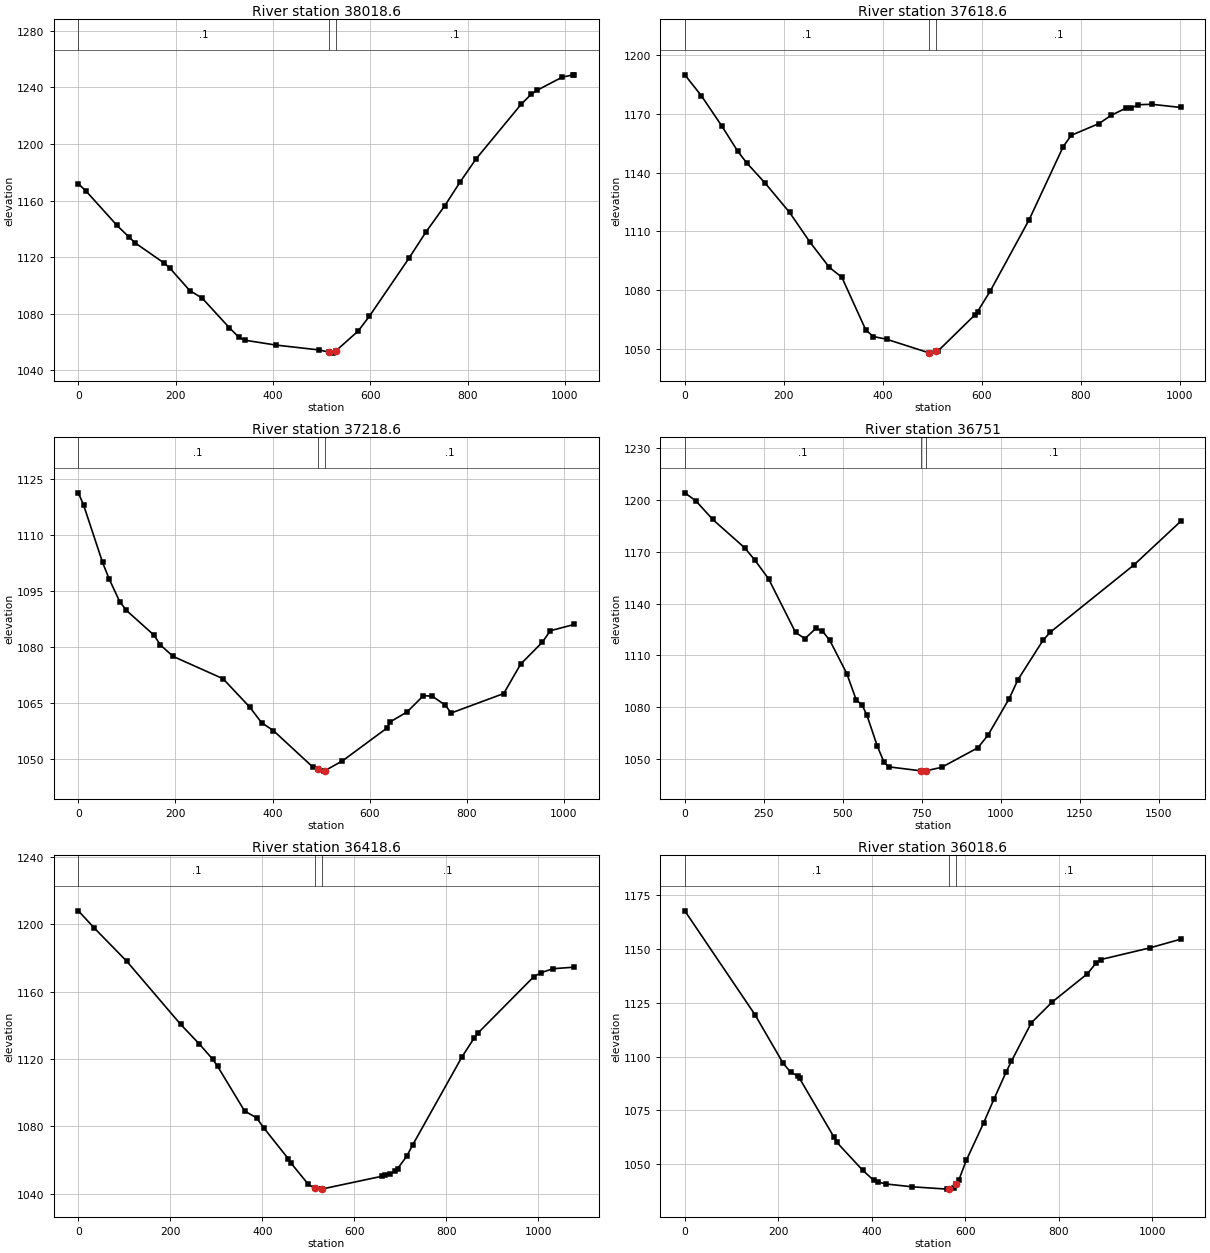
Type RM Length L Ch R = 1 ,38018.6,402.474,400,396.597
XS GIS Cut Line= 3
     1705389.523      336158.055     1704902.402      335968.658
     1704437.761      335793.780
#Sta/Elev= 30
       0 1171.74    15.0 1166.99    79.5 1142.38   104.9 1133.95   117.0 1129.99
   175.2 1116.07   187.9 1112.32   229.0 1096.39   254.6 1091.01   310.2 1070.19
   329.5 1063.56   342.0 1061.33   405.3 1057.91   494.9 1054.42   515.1 1052.93
   522.5 1052.18   530.1 1053.99   575.3 1067.84   598.1 1078.19   679.3 1119.08
   713.9 1137.45   752.9 1156.16   784.9 1173.16   817.4 1189.37   910.7 1228.21
   930.5 1234.90   942.8 1237.85   994.3 1247.10  1016.9 1248.78  1019.1 1248.51
#Mann= 3 , 0 , 0
       0     0.1       0   515.1   0.045       0   530.1     0.1       0
Bank Sta=   515.1,   530.1
Exp/Cntr=0.3,0.1

Type RM Length L Ch R = 1 ,37618.6,395.164,400,400.155
XS GIS Cut Line= 3
     1705526.429      335735.255     1705043.702      335603.228
     1704554.303      335496.397
#Sta/Elev= 30
       0 1189.95    33.4 1179.29    74.7 1163.80   107.0 1150.84   125.2 1144.88
   161.7 1134.74   211.5 1119.63   253.0 1104.33   291.9 1091.50   317.2 1086.43
   365.7 1059.39   380.9 1056.11   407.5 1054.75     493 1047.80   495.9 1047.64
     508 1048.65   512.3 1048.96   586.2 1067.26   591.3 1068.90   616.7 1079.29
   695.5 1115.88   764.3 1153.23   780.4 1159.01   836.4 1165.01   861.2 1169.25
   890.5 1172.87   902.1 1172.91   914.8 1174.65   943.0 1174.89  1001.4 1173.26
#Mann= 3 , 0 , 0
       0     0.1       0     493   0.045       0     508     0.1       0
Bank Sta=     493,     508
Exp/Cntr=0.3,0.1

Type RM Length L Ch R = 1 ,37218.6,460.993,467.608,480.139
XS GIS Cut Line= 3
     1705580.214      335453.119     1705132.812      335227.652
     1704627.362      335104.025
#Sta/Elev= 30
       0 1121.30    10.7 1118.09    49.9 1102.65    63.4 1098.23    85.3 1092.12
    99.2 1089.76   156.0 1083.13   169.0 1080.51   195.4 1077.44   298.2 1071.45
   353.1 1063.85   377.6 1059.66   401.7 1057.57   482.9 1047.80   493.5 1047.30
   506.3 1046.69   508.5 1046.85   544.0 1049.43   635.7 1058.23   642.3 1059.89
   677.1 1062.54   710.7 1066.90   728.7 1066.81   756.1 1064.36   768.0 1062.27
   876.3 1067.49   911.2 1075.38   955.9 1081.25   972.3 1084.33  1021.4 1086.01
#Mann= 3 , 0 , 0
       0     0.1       0   493.5   0.045       0   508.5     0.1       0
Bank Sta=   493.5,   508.5
Exp/Cntr=0.3,0.1

Type RM Length L Ch R = 1 ,36751,336.173,332.392,325.816
XS GIS Cut Line= 3
     1705833.657      335365.311     1705295.275      334856.031
     1704713.241      334266.722
#Sta/Elev= 30
       0 1204.07    34.9 1199.46    88.5 1188.64   189.4 1172.28   222.1 1165.06
   265.2 1154.31   350.6 1123.26   380.3 1119.71   414.8 1125.58   435.3 1124.14
   458.9 1118.70   512.7 1099.48   542.5 1084.29   561.4 1081.16   576.1 1075.58
   609.7 1057.29   630.7 1048.16   645.2 1045.51   748.1 1043.17   756.4 1043.02
   763.1 1043.20   812.9 1045.21   927.7 1056.54   959.9 1063.91  1026.7 1084.95
  1054.7 1096.00  1133.8 1118.72  1156.9 1123.42  1421.0 1162.23  1569.4 1187.53
#Mann= 3 , 0 , 0
       0     0.1       0   748.1   0.045       0   763.1     0.1       0
Bank Sta=   748.1,   763.1
Exp/Cntr=0.3,0.1

Type RM Length L Ch R = 1 ,36418.6,396.339,400,398.332
XS GIS Cut Line= 3
     1705920.962      334972.438     1705476.493      334699.866
     1705010.069      334396.731
#Sta/Elev= 30
       0 1208.03    34.3 1197.92   105.6 1177.98   222.5 1140.59   263.3 1128.88
   292.3 1119.85   302.7 1115.72   361.4 1089.19   387.3 1085.18   403.1 1079.15
   456.5 1060.81   462.6 1058.17   499.0 1045.96   513.9 1043.21   528.6 1042.82
   528.9 1042.85   660.2 1050.47   665.6 1051.23   678.4 1051.92   688.5 1053.43
   694.0 1055.03   713.6 1062.26   726.8 1069.10   833.6 1121.19   860.1 1132.44
   868.4 1135.41   990.1 1168.97  1005.9 1171.31  1031.7 1173.67  1077.7 1174.59
#Mann= 3 , 0 , 0
       0     0.1       0   513.9   0.045       0   528.9     0.1       0
Bank Sta=   513.9,   528.9
Exp/Cntr=0.3,0.1

Type RM Length L Ch R = 1 ,36018.6,532.5,561.49,579.962
XS GIS Cut Line= 3
     1706011.084      334715.228     1705589.904      334325.786
     1705176.062      334068.442
#Sta/Elev= 30
       0 1167.79   149.9 1119.60   210.2 1097.02   226.4 1092.79   241.9 1091.02
   245.5 1089.94   319.2 1062.62   325.2 1060.20   380.5 1047.23   404.6 1042.46
   414.0 1041.68   431.6 1040.80   485.6 1039.53   561.1 1038.43   566.1 1038.66
   576.1 1039.11   581.1 1040.85   586.7 1042.84   602.4 1051.82   639.2 1069.07
   661.5 1080.25   687.9 1093.00   698.7 1097.81   741.5 1115.73   786.2 1125.41
   861.4 1138.51   879.7 1143.41   890.5 1145.16   995.3 1150.57  1061.0 1154.60
#Mann= 3 , 0 , 0
       0     0.1       0   566.1   0.045       0   581.1     0.1       0
Bank Sta=   566.1,   581.1
Exp/Cntr=0.3,0.1

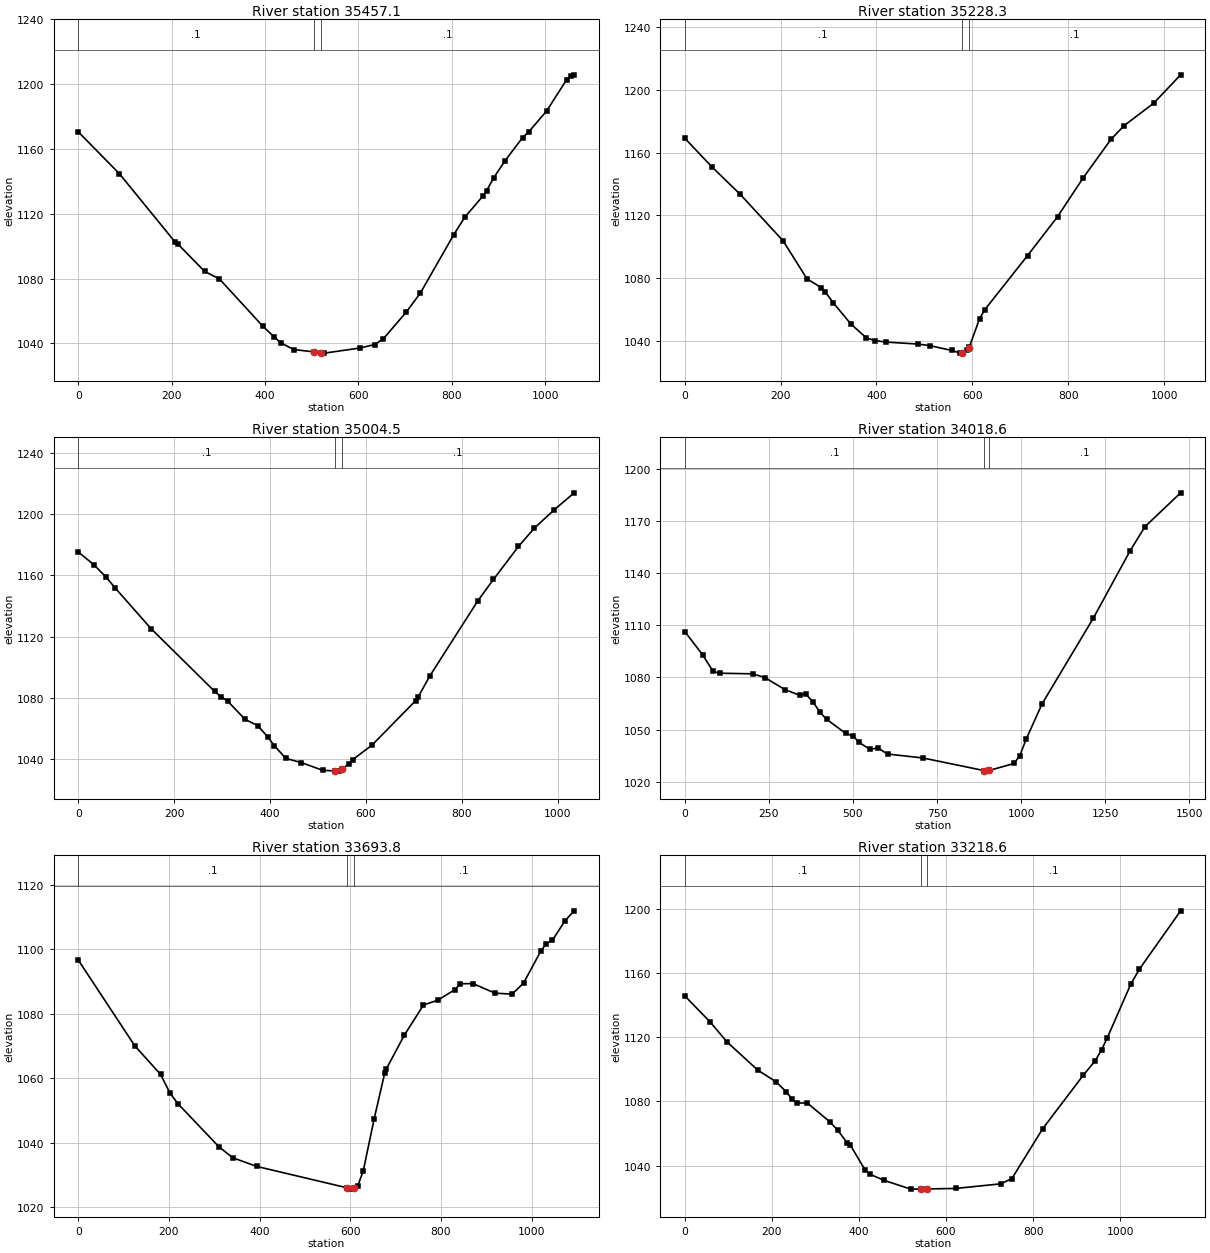
Type RM Length L Ch R = 1 ,35457.1,232.439,228.806,225.928
XS GIS Cut Line= 3
     1706204.055      334587.855     1706000.200      334116.433
     1705772.616      333617.004
#Sta/Elev= 30
       0 1170.54    88.1 1144.71   207.8 1102.40   213.8 1101.17   270.4 1084.48
   302.3 1079.81   394.9 1050.74   419.5 1044.04   433.7 1040.37   461.8 1036.19
   504.4 1034.79   519.4 1034.30   527.4 1034.00   604.1 1037.19   634.9 1039.31
   653.6 1042.86   702.0 1059.09   732.9 1071.10   803.9 1106.87   828.0 1117.88
   867.1 1131.03   874.9 1134.31   889.6 1142.02   914.2 1152.74   951.9 1167.05
   965.7 1170.78  1003.8 1183.64  1046.3 1202.84  1055.3 1205.01  1062.4 1205.79
#Mann= 3 , 0 , 0
       0     0.1       0   504.4   0.045       0   519.4     0.1       0
Bank Sta=   504.4,   519.4
Exp/Cntr=0.3,0.1

Type RM Length L Ch R = 1 ,35228.3,230.979,223.835,219.011
XS GIS Cut Line= 3
     1706374.946      334460.256     1706140.614      333971.874
     1705969.748      333509.449
#Sta/Elev= 30
       0 1169.13    56.4 1150.97   115.9 1133.32   205.2 1103.76   255.1 1079.54
   284.4 1074.06   293.3 1071.13   310.1 1064.20   346.7 1050.77   379.0 1041.91
   397.7 1040.20   420.5 1039.27   487.2 1038.01   511.7 1036.99   557.5 1033.93
   574.9 1032.25   577.7 1032.40   580.7 1032.55   588.7 1034.17   592.7 1035.76
   593.7 1036.15   615.0 1054.20   625.7 1059.83   715.1 1094.36   777.7 1119.14
   830.9 1143.76   889.4 1168.51   916.8 1177.21   978.3 1191.44  1034.6 1209.55
#Mann= 3 , 0 , 0
       0     0.1       0   577.7   0.045       0   592.7     0.1       0
Bank Sta=   577.7,   592.7
Exp/Cntr=0.3,0.1

Type RM Length L Ch R = 1 ,35004.5,995.191,985.869,893.18
XS GIS Cut Line= 3
     1706664.874      334291.284     1706337.159      333859.971
     1706076.831      333441.330
#Sta/Elev= 30
       0 1175.33    32.9 1166.87    58.5 1158.70    76.3 1152.00   151.5 1125.25
   284.7 1084.04   297.1 1080.73   311.7 1077.71   348.1 1065.75   374.1 1061.73
   395.4 1054.29   409.1 1048.49   433.3 1040.18   465.0 1037.53   510.2 1032.42
   535.1 1032.05   543.8 1031.91   550.1 1033.34   564.3 1036.56   572.7 1039.47
   612.5 1048.83   704.0 1078.06   708.5 1080.14   733.9 1094.38   833.9 1143.51
   866.3 1157.38   918.5 1178.96   951.9 1191.06   993.5 1203.05  1034.7 1214.07
#Mann= 3 , 0 , 0
       0     0.1       0   535.1   0.045       0   550.1     0.1       0
Bank Sta=   535.1,   550.1
Exp/Cntr=0.3,0.1

Type RM Length L Ch R = 1 ,34018.6,320.122,324.822,327.779
XS GIS Cut Line= 3
     1707623.411      333750.167     1706764.623      333488.273
     1706224.992      333286.037
#Sta/Elev= 30
       0 1106.45    53.0 1093.04    84.2 1083.49   103.5 1082.45   203.0 1082.09
   238.7 1079.86   298.0 1072.99   342.0 1069.71   358.9 1070.57   382.4 1065.65
   401.8 1059.92   421.4 1055.93   478.5 1047.81   500.7 1046.27   517.7 1042.66
   550.3 1038.62   574.3 1039.39   602.7 1035.92   707.8 1033.66   890.3 1026.37
   897.0 1026.08   905.3 1026.47   978.9 1030.50   996.2 1035.07  1015.0 1044.55
  1062.7 1064.98  1214.4 1114.09  1323.3 1152.71  1368.0 1166.81  1474.1 1186.30
#Mann= 3 , 0 , 0
       0     0.1       0   890.3   0.045       0   905.3     0.1       0
Bank Sta=   890.3,   905.3
Exp/Cntr=0.3,0.1

Type RM Length L Ch R = 1 ,33693.8,484.929,475.178,475.467
XS GIS Cut Line= 3
     1707314.125      333464.775     1706764.911      333248.162
     1706291.752      333075.910
#Sta/Elev= 30
       0 1096.70   124.7 1070.07   181.4 1061.24   202.1 1055.46   219.7 1052.13
   310.3 1038.75   340.6 1035.36   393.6 1032.67   593.7 1026.00   599.7 1025.62
   608.7 1026.06   616.0 1026.45   628.6 1031.30   652.6 1047.40   675.9 1061.60
   679.2 1062.85   719.4 1073.44   761.5 1082.77   792.9 1084.25   830.8 1087.54
   842.7 1089.36   870.6 1089.42   919.2 1086.45   957.1 1086.14   982.4 1089.61
  1020.3 1099.49  1032.4 1101.81  1045.6 1102.80  1073.9 1108.94  1093.9 1112.00
#Mann= 3 , 0 , 0
       0     0.1       0   593.7   0.045       0   608.7     0.1       0
Bank Sta=   593.7,   608.7
Exp/Cntr=0.3,0.1

Type RM Length L Ch R = 1 ,33218.6,480.393,492.709,488.644
XS GIS Cut Line= 3
     1707499.729      333277.264     1707012.102      333023.615
     1706528.356      332687.361
#Sta/Elev= 30
       0 1145.65    58.6 1129.33    96.9 1117.03   167.4 1099.49   209.4 1092.23
   232.4 1086.13   247.0 1081.26   257.9 1078.94   281.3 1079.01   333.5 1067.18
   351.5 1061.99   373.6 1053.98   379.8 1052.96   413.8 1037.47   424.7 1034.72
   458.3 1030.77   519.2 1025.38   542.2 1025.45   557.2 1025.49   622.9 1025.82
   725.6 1028.67   751.1 1031.91   822.2 1063.07   915.5 1096.39   942.6 1105.28
   957.4 1112.17   970.6 1119.72  1024.6 1153.14  1044.2 1162.33  1138.8 1198.63
#Mann= 3 , 0 , 0
       0     0.1       0   542.2   0.045       0   557.2     0.1       0
Bank Sta=   542.2,   557.2
Exp/Cntr=0.3,0.1

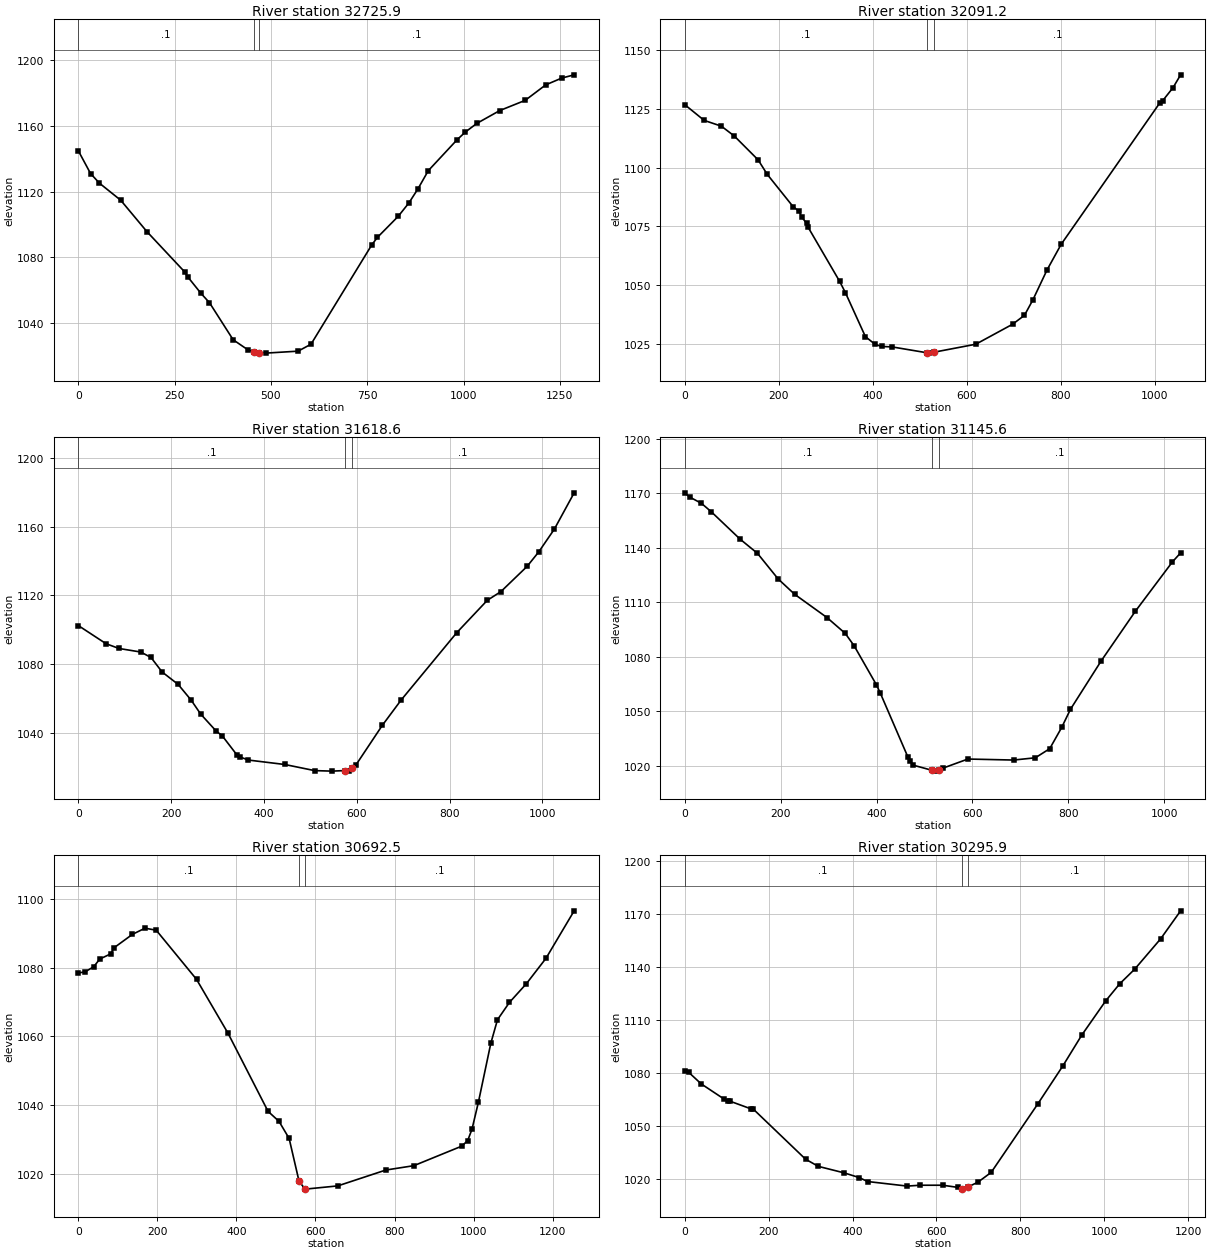
Type RM Length L Ch R = 1 ,32725.9,619.813,634.689,637.861
XS GIS Cut Line= 3
     1707547.992      332934.987     1706978.518      332631.808
     1706374.657      332413.545
#Sta/Elev= 30
       0 1144.86    31.7 1131.01    54.8 1125.11   110.0 1114.72   178.1 1095.55
   276.2 1070.95   283.5 1068.13   318.6 1057.84   340.5 1052.19   401.9 1029.60
   441.4 1023.26   455.3 1022.36   470.3 1021.51   486.1 1021.44   570.5 1022.64
   604.1 1026.89   762.0 1087.55   776.6 1092.08   830.4 1104.88   858.2 1113.07
   881.7 1121.66   908.5 1132.74   983.0 1151.54  1004.2 1156.20  1034.5 1161.58
  1093.9 1169.39  1160.1 1175.64  1213.3 1185.07  1255.1 1189.24  1287.2 1191.21
#Mann= 3 , 0 , 0
       0     0.1       0   455.3   0.045       0   470.3     0.1       0
Bank Sta=   455.3,   470.3
Exp/Cntr=0.3,0.1

Type RM Length L Ch R = 1 ,32091.2,479.899,472.602,466.094
XS GIS Cut Line= 3
     1707656.443      332786.096     1707315.338      332381.508
     1706902.940      332055.762
#Sta/Elev= 30
       0 1126.86    41.2 1120.17    77.8 1117.71   105.3 1113.52   155.9 1103.38
   175.5 1097.16   230.1 1083.51   242.9 1081.50   248.8 1079.02   258.9 1076.36
   261.6 1074.92   329.4 1051.63   341.6 1046.85   384.2 1028.10   404.9 1024.81
   418.5 1023.93   440.9 1023.74   515.2 1021.24   520.5 1021.09   530.2 1021.49
   619.0 1024.88   697.2 1033.38   722.5 1037.18   740.3 1043.71   770.5 1056.49
   800.6 1067.42  1010.5 1127.64  1016.8 1128.63  1038.5 1134.09  1054.7 1139.57
#Mann= 3 , 0 , 0
       0     0.1       0   515.2   0.045       0   530.2     0.1       0
Bank Sta=   515.2,   530.2
Exp/Cntr=0.3,0.1

Type RM Length L Ch R = 1 ,31618.6,473.956,473.002,469.426
XS GIS Cut Line= 3
     1707978.069      332359.846     1707489.484      332043.025
     1707056.978      331821.225
#Sta/Elev= 30
       0 1102.53    59.9 1091.96    87.7 1089.22   134.6 1087.15   156.6 1083.99
   180.4 1075.60   215.1 1068.34   243.1 1059.22   263.7 1051.10   297.0 1041.25
   310.1 1038.49   341.1 1027.61   348.6 1026.20   366.4 1024.41   444.9 1021.83
   509.2 1018.28   546.6 1017.98   574.8 1018.31   584.0 1018.27   589.8 1019.55
   598.6 1021.73   655.0 1044.57   695.8 1059.36   815.6 1098.46   881.2 1117.19
   910.6 1122.26   967.0 1136.90   992.1 1145.33  1025.8 1158.58  1068.4 1179.63
#Mann= 3 , 0 , 0
       0     0.1       0   574.8   0.045       0   589.8     0.1       0
Bank Sta=   574.8,   589.8
Exp/Cntr=0.3,0.1

Type RM Length L Ch R = 1 ,31145.6,464.181,453.089,446.446
XS GIS Cut Line= 3
     1708215.559      332075.137     1707761.645      331778.526
     1707350.459      331507.465
#Sta/Elev= 30
       0 1170.30    10.0 1167.99    34.8 1164.50    55.4 1159.83   115.4 1144.78
   151.6 1136.97   194.7 1122.88   229.1 1114.43   296.5 1101.63   334.7 1092.89
   353.2 1086.08   399.8 1064.55   407.8 1060.05   465.7 1024.63   469.2 1022.85
   477.1 1020.27   514.7 1017.56   527.0 1017.03   529.7 1017.42   538.3 1018.65
   590.6 1023.69   686.0 1023.13   731.3 1024.38   761.3 1029.39   786.4 1041.14
   804.5 1051.05   868.8 1077.79   939.8 1105.02  1017.4 1132.31  1034.4 1137.23
#Mann= 3 , 0 , 0
       0     0.1       0   514.7   0.045       0   529.7     0.1       0
Bank Sta=   514.7,   529.7
Exp/Cntr=0.3,0.1

Type RM Length L Ch R = 1 ,30692.5,391.776,396.666,407.202
XS GIS Cut Line= 3
     1708540.115      331771.251     1708038.111      331545.713
     1707368.772      331327.450
#Sta/Elev= 30
       0 1078.45    17.0 1078.78    38.7 1080.25    54.3 1082.51    81.7 1084.01
    90.8 1085.83   137.0 1089.71   168.8 1091.50   197.1 1090.90   299.0 1076.60
   378.8 1060.88   480.0 1038.15   507.6 1035.26   533.3 1030.27   558.5 1017.75
   573.5 1015.58   574.1 1015.51   656.3 1016.45   777.9 1021.07   848.9 1022.34
   970.3 1028.04   985.1 1029.67   996.0 1032.99  1012.2 1040.85  1043.5 1057.96
  1060.4 1064.84  1090.8 1069.90  1133.4 1075.31  1183.1 1082.72  1254.4 1096.55
#Mann= 3 , 0 , 0
       0     0.1       0   558.5   0.045       0   573.5     0.1       0
Bank Sta=   558.5,   573.5
Exp/Cntr=0.3,0.1

Type RM Length L Ch R = 1 ,30295.9,320.682,326.483,327.458
XS GIS Cut Line= 3
     1708441.368      331676.432     1707961.190      331152.601
     1707690.617      330766.633
#Sta/Elev= 30
       0 1081.06     9.6 1080.50    39.2 1074.01    93.9 1065.40   102.8 1064.25
   108.7 1064.15   157.5 1059.92   163.2 1059.77   287.8 1031.44   318.2 1027.37
   379.3 1023.72   415.6 1021.04   435.7 1018.79   530.2 1016.21   560.6 1016.69
   614.6 1016.70   650.5 1015.49   659.9 1014.56   660.6 1014.49   674.9 1015.74
   698.6 1018.38   730.4 1023.96   840.9 1062.47   901.1 1084.15   946.5 1101.68
  1003.3 1120.96  1036.6 1130.59  1072.5 1138.91  1134.4 1156.09  1182.0 1171.92
#Mann= 3 , 0 , 0
       0     0.1       0   659.9   0.045       0   674.9     0.1       0
Bank Sta=   659.9,   674.9
Exp/Cntr=0.3,0.1