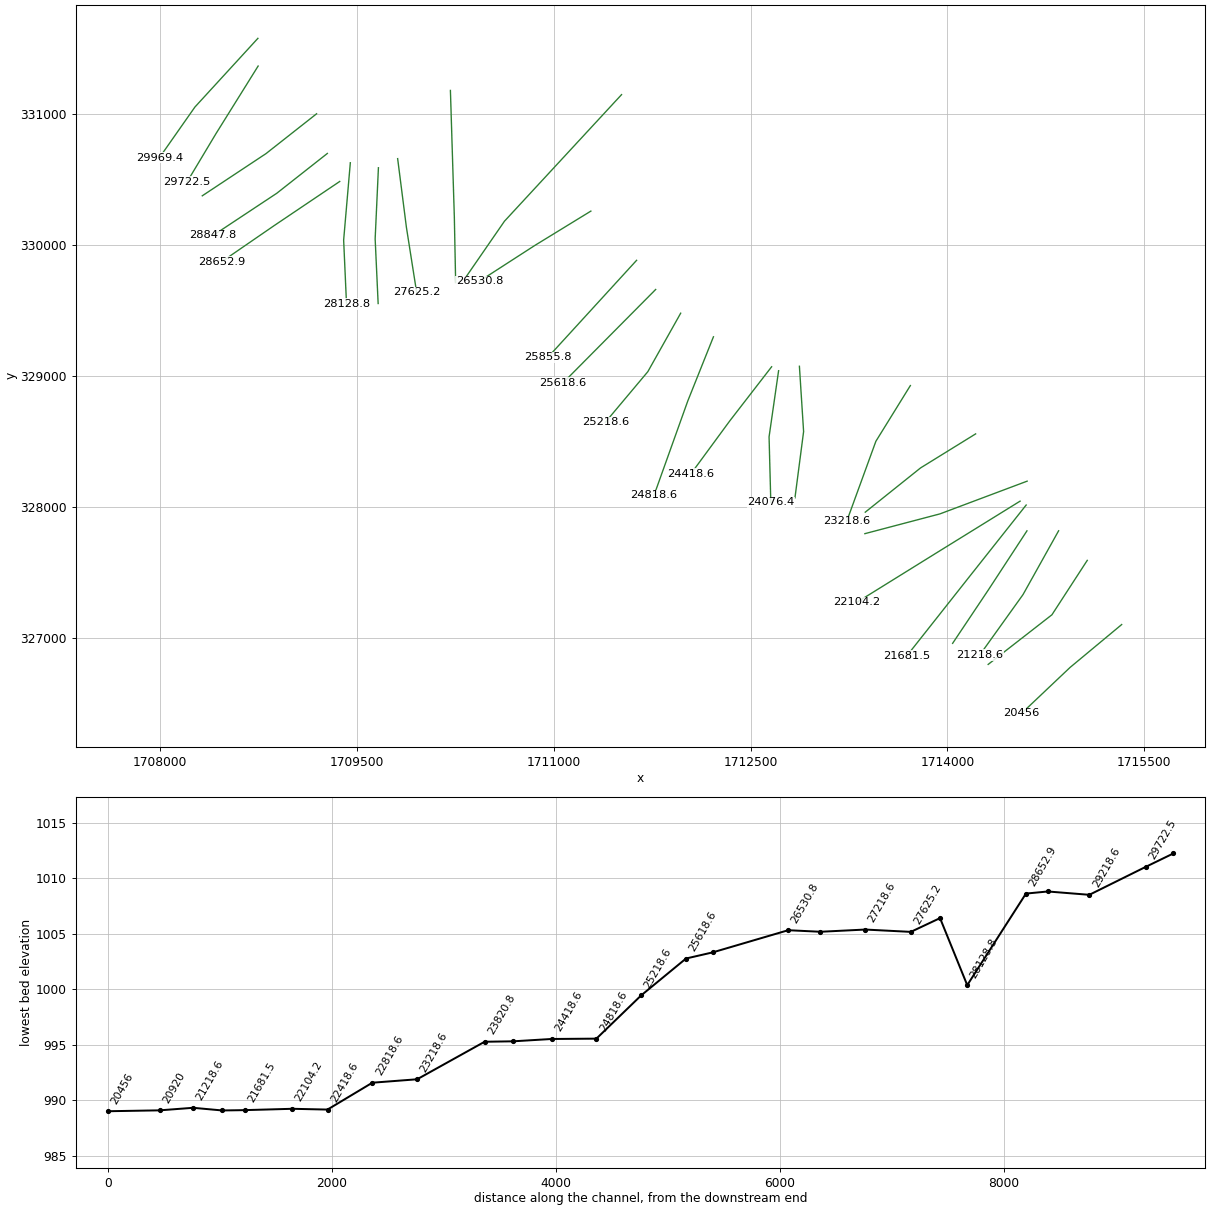
HEC-RAS study JonesCr.prj: JonesCr

--- JonesCr.g01 (geometry) --- (continued)

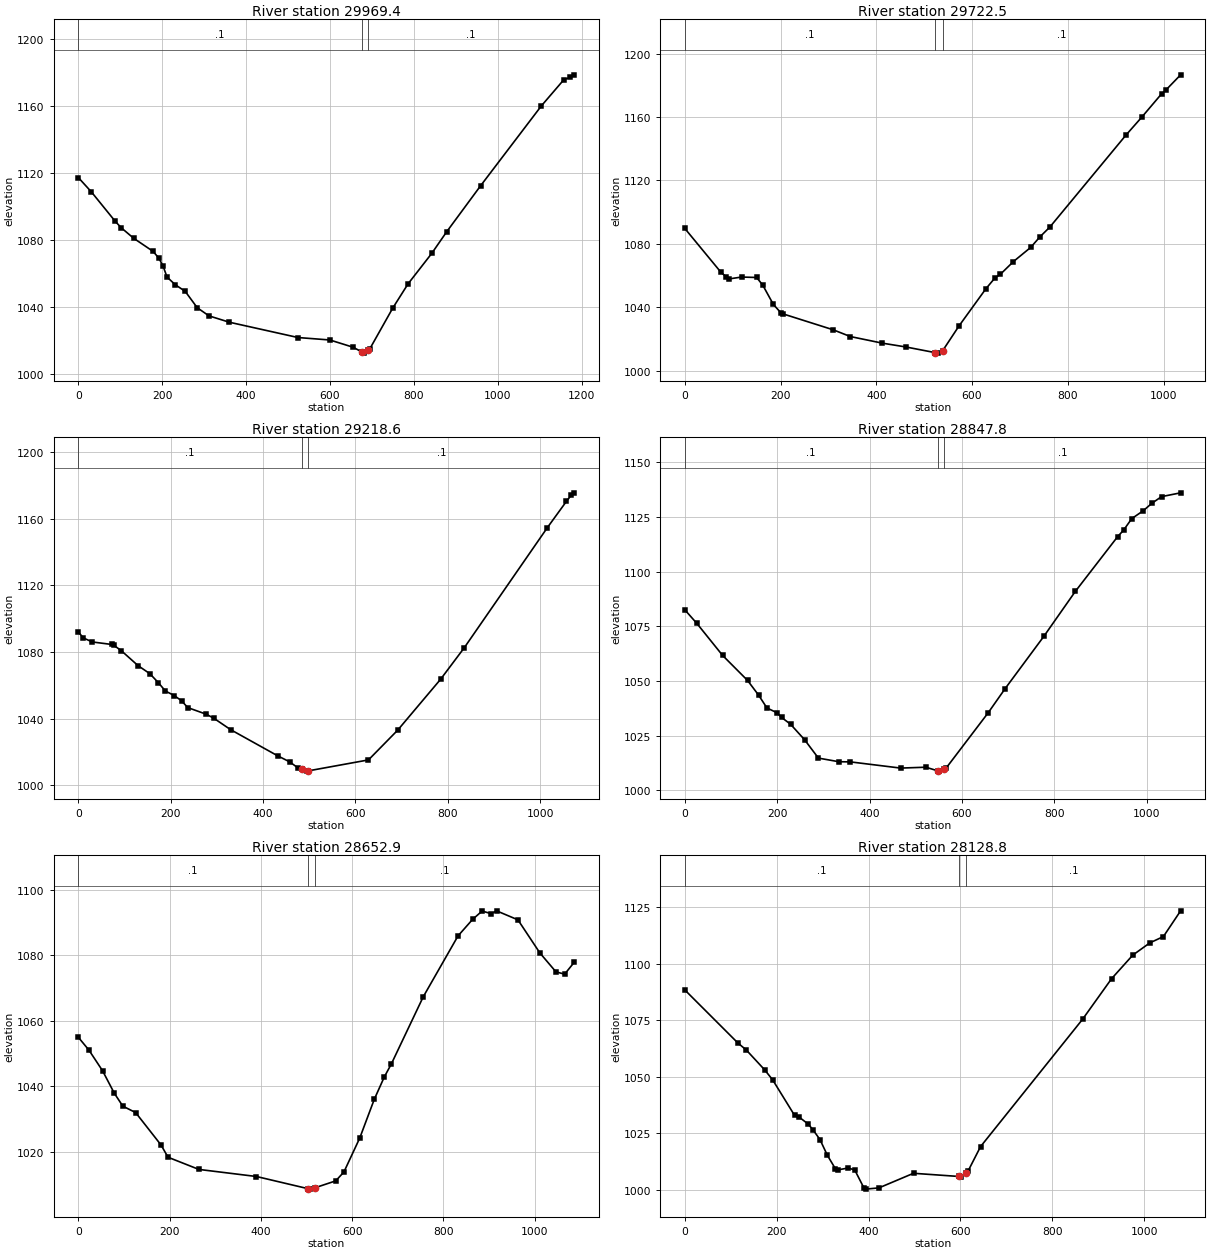
Type RM Length L Ch R = 1 ,29969.4,242.66,246.901,251.143
XS GIS Cut Line= 3
     1708743.827      331574.815     1708263.649      331050.984
     1707993.076      330665.016
#Sta/Elev= 30
       0 1117.19    31.0 1108.65    88.0 1091.02   102.4 1087.15   131.7 1080.94
   178.0 1073.08   192.1 1069.00   202.2 1064.12   211.4 1057.73   230.7 1053.19
   254.8 1049.15   283.4 1039.39   311.4 1034.50   360.0 1030.70   523.8 1021.54
   599.7 1020.08   654.2 1015.81   675.2 1013.07   681.7 1012.22   690.2 1013.81
   694.6 1014.66   749.4 1039.09   786.0 1053.63   842.3 1071.79   878.3 1084.85
   959.2 1112.37  1104.0 1160.11  1157.8 1175.82  1172.8 1177.07  1182.0 1178.62
#Mann= 3 , 0 , 0
       0     0.1       0   675.2   0.045       0   690.2     0.1       0
Bank Sta=   675.2,   690.2
Exp/Cntr=0.3,0.1

Type RM Length L Ch R = 1 ,29722.5,511.807,503.858,493.955
XS GIS Cut Line= 3
     1708745.653      331363.534     1708423.708      330847.272
     1708204.136      330480.668
#Sta/Elev= 30
       0 1089.73    75.2 1062.16    86.7 1059.09    93.0 1057.88   118.6 1059.04
   150.1 1058.76   162.9 1053.91   184.8 1041.85   200.8 1036.41   204.6 1035.83
   309.6 1025.78   345.9 1021.47   412.7 1017.30   461.6 1014.91   523.6 1011.29
   529.3 1011.01   538.6 1012.53   573.1 1028.32   629.0 1051.67   648.2 1058.60
   658.8 1060.67   686.6 1068.85   722.4 1077.72   741.9 1084.44   762.6 1090.62
   921.8 1148.75   954.6 1159.99   996.3 1174.84  1004.9 1177.09  1035.7 1186.70
#Mann= 3 , 0 , 0
       0     0.1       0   523.6   0.045       0   538.6     0.1       0
Bank Sta=   523.6,   538.6
Exp/Cntr=0.3,0.1

Type RM Length L Ch R = 1 ,29218.6,372.521,370.868,368.678
XS GIS Cut Line= 3
     1709191.218      330999.624     1708805.698      330696.070
     1708319.799      330374.386
#Sta/Elev= 30
       0 1091.99    10.9 1088.40    30.1 1085.99    72.7 1084.47    76.5 1084.04
    92.7 1080.83   129.3 1071.78   154.7 1066.98   173.3 1061.54   188.5 1056.55
   207.5 1053.85   223.8 1050.62   236.8 1046.62   277.3 1042.59   293.3 1040.22
   329.6 1033.39   431.4 1017.70   457.4 1014.07   475.9 1010.35   483.2 1009.55
   494.3 1008.49   498.2 1008.67   628.1 1015.22   691.3 1033.05   784.1 1063.55
   835.5 1082.52  1015.4 1154.59  1056.5 1170.28  1066.9 1173.98  1073.4 1175.46
#Mann= 3 , 0 , 0
       0     0.1       0   483.2   0.045       0   498.2     0.1       0
Bank Sta=   483.2,   498.2
Exp/Cntr=0.3,0.1

Type RM Length L Ch R = 1 ,28847.8,195.352,194.856,194.359
XS GIS Cut Line= 3
     1709273.188      330697.206     1708887.667      330393.653
     1708401.768      330071.969
#Sta/Elev= 30
       0 1082.59    25.8 1076.44    81.9 1061.71   135.8 1050.29   159.6 1043.60
   177.8 1037.69   199.6 1035.49   209.6 1033.34   228.9 1030.25   259.4 1023.13
   289.2 1014.75   333.6 1013.09   358.4 1013.02   467.1 1010.18   521.7 1010.58
   547.1 1008.96   549.7 1008.79   562.1 1009.77   565.1 1010.01   656.8 1035.49
   693.6 1046.57   777.4 1070.48   845.5 1091.02   937.3 1116.12   949.8 1119.00
   967.7 1124.31   992.5 1127.91  1011.3 1131.34  1032.1 1134.36  1073.4 1136.10
#Mann= 3 , 0 , 0
       0     0.1       0   547.1   0.045       0   562.1     0.1       0
Bank Sta=   547.1,   562.1
Exp/Cntr=0.3,0.1

Type RM Length L Ch R = 1 ,28652.9,502.072,524.11,547.519
XS GIS Cut Line= 3
     1709367.529      330483.635     1708866.358      330146.150
     1708469.031      329872.934
#Sta/Elev= 30
       0 1054.93    23.4 1050.98    53.1 1044.71    78.8 1037.86    97.5 1033.92
   125.6 1031.95   181.3 1022.05   196.5 1018.33   264.2 1014.61   390.3 1012.45
   502.6 1008.76   507.0 1008.60   517.6 1008.97   564.0 1011.12   582.0 1013.85
   616.7 1024.22   648.5 1036.02   670.5 1042.85   685.9 1046.81   755.8 1067.30
   832.0 1085.87   864.0 1090.92   884.7 1093.44   904.9 1092.64   916.4 1093.51
   963.2 1090.76  1011.4 1080.64  1046.5 1074.89  1065.6 1074.19  1086.4 1077.79
#Mann= 3 , 0 , 0
       0     0.1       0   502.6   0.045       0   517.6     0.1       0
Bank Sta=   502.6,   517.6
Exp/Cntr=0.3,0.1

Type RM Length L Ch R = 1 ,28128.8,243.504,242.861,242.629
XS GIS Cut Line= 3
     1709448.476      330626.410     1709397.548      330037.100
     1709419.374      329549.647
#Sta/Elev= 30
       0 1088.51   116.1 1064.92   133.6 1061.98   173.7 1053.17   191.2 1048.73
   238.9 1033.01   249.4 1032.15   268.8 1029.12   280.0 1026.35   294.3 1022.27
   310.4 1015.31   327.6 1009.44   334.2 1008.90   355.7 1009.70   370.0 1008.82
   389.7 1000.97   393.8 1000.35   422.6 1000.90   497.9 1007.36     597 1005.95
   600.6 1005.89     612 1007.48   616.3 1008.21   643.9 1019.18   865.9 1075.51
   929.1 1093.48   975.2 1103.90  1012.3 1109.32  1041.9 1112.12  1079.4 1123.51
#Mann= 3 , 0 , 0
       0     0.1       0     597   0.045       0     612     0.1       0
Bank Sta=     597,     612
Exp/Cntr=0.3,0.1

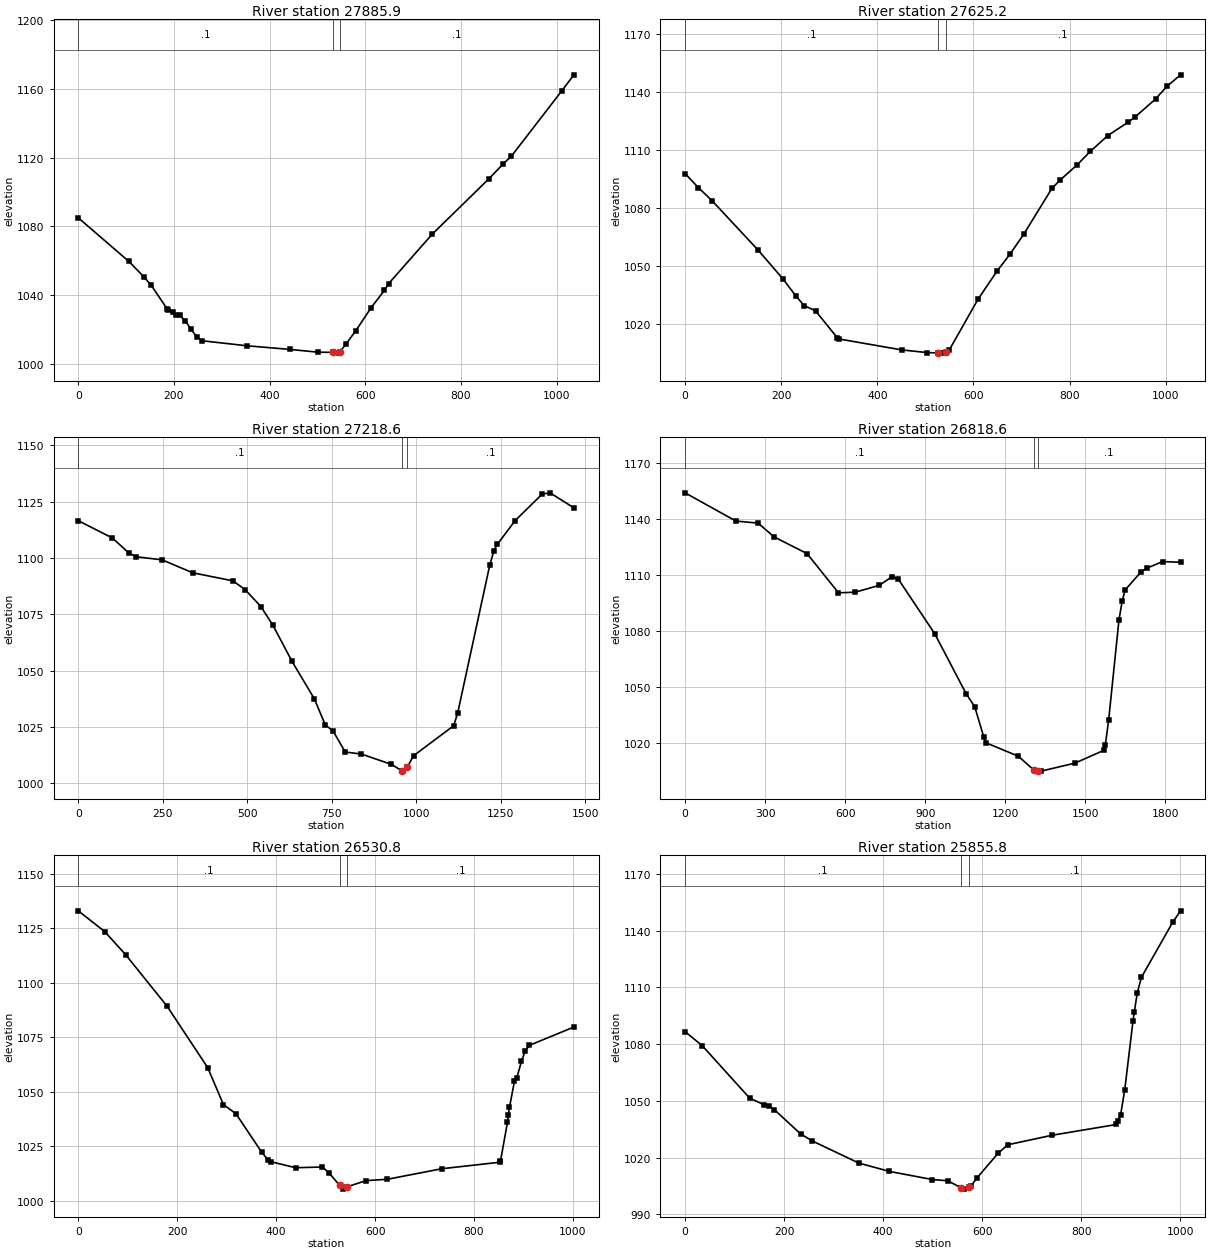
Type RM Length L Ch R = 1 ,27885.9,261.614,260.737,262.007
XS GIS Cut Line= 3
     1709662.650      330588.253     1709637.728      330046.145
     1709660.526      329553.225
#Sta/Elev= 30
       0 1084.98   105.8 1059.62   136.6 1050.85   152.5 1045.80   185.8 1032.02
   188.2 1031.21   197.2 1030.18   204.4 1028.72   211.9 1028.29   223.8 1025.13
   235.2 1020.40   247.6 1015.81   259.5 1013.55   352.7 1010.65   441.8 1008.57
   500.5 1006.95   531.5 1006.80   544.7 1006.39   546.5 1007.02   559.5 1011.59
   580.4 1019.53   612.4 1032.88   639.8 1042.81   648.9 1046.80   739.7 1075.43
   857.9 1107.53   888.0 1116.23   905.6 1120.86  1011.1 1158.85  1036.1 1168.06
#Mann= 3 , 0 , 0
       0     0.1       0   531.5   0.045       0   546.5     0.1       0
Bank Sta=   531.5,   546.5
Exp/Cntr=0.3,0.1

Type RM Length L Ch R = 1 ,27625.2,404.302,406.567,404.659
XS GIS Cut Line= 3
     1709809.241      330657.781     1709876.043      330133.838
     1709954.166      329637.264
#Sta/Elev= 30
       0 1098.08    27.6 1090.79    56.4 1083.94   152.0 1058.43   203.3 1043.64
   231.0 1034.56   247.6 1029.77   271.5 1027.00   316.5 1013.14   319.4 1012.51
   450.8 1006.81   503.9 1005.43   527.1 1005.25   534.9 1005.15   542.1 1005.59
   549.6 1006.79   610.0 1033.26   649.7 1047.84   675.6 1056.24   704.3 1066.58
   763.2 1090.40   779.2 1094.46   815.3 1102.49   843.1 1109.53   879.4 1117.70
   921.4 1124.56   936.9 1127.48   978.7 1136.62  1002.7 1143.26  1030.9 1149.13
#Mann= 3 , 0 , 0
       0     0.1       0   527.1   0.045       0   542.1     0.1       0
Bank Sta=   527.1,   542.1
Exp/Cntr=0.3,0.1

Type RM Length L Ch R = 1 ,27218.6,417.83,400,385.637
XS GIS Cut Line= 3
     1710211.471      331177.609     1710241.341      330212.784
     1710251.384      329712.384
#Sta/Elev= 30
       0 1116.50   100.7 1108.84   149.8 1102.14   171.9 1100.48   247.8 1099.13
   338.2 1093.40   457.0 1089.82   493.0 1085.97   540.1 1078.39   575.8 1070.05
   632.0 1054.08   697.9 1037.51   730.2 1025.98   753.9 1023.06   789.6 1013.83
   837.0 1012.95   925.9 1008.37   957.8 1005.42   958.8 1005.36   972.8 1007.06
   991.5 1012.18  1110.2 1025.51  1122.1 1031.17  1217.1 1096.88  1229.0 1103.06
  1239.2 1106.00  1292.0 1116.54  1372.0 1128.33  1395.3 1128.88  1465.8 1122.21
#Mann= 3 , 0 , 0
       0     0.1       0   957.8   0.045       0   972.8     0.1       0
Bank Sta=   957.8,   972.8
Exp/Cntr=0.3,0.1

Type RM Length L Ch R = 1 ,26818.6,293.507,287.807,278.884
XS GIS Cut Line= 3
     1711516.140      331145.788     1710623.580      330180.836
     1710315.319      329734.132
#Sta/Elev= 30
       0 1154.07   190.5 1138.96   273.4 1137.88   333.9 1130.48   457.3 1121.53
   574.9 1100.57   637.7 1100.89   728.0 1104.59   775.3 1109.16   797.9 1108.15
   935.6 1078.68  1053.6 1046.53  1085.5 1039.65  1119.4 1023.40  1129.4 1020.22
  1249.1 1013.12    1307 1005.75    1322 1005.49  1334.3 1005.16  1461.5 1009.46
  1570.3 1016.33  1574.9 1019.12  1587.3 1032.29  1626.1 1086.10  1638.3 1096.29
  1649.5 1102.16  1708.4 1111.71  1731.0 1113.78  1789.4 1117.29  1857.2 1116.91
#Mann= 3 , 0 , 0
       0     0.1       0    1307   0.045       0    1322     0.1       0
Bank Sta=    1307,    1322
Exp/Cntr=0.3,0.1

Type RM Length L Ch R = 1 ,26530.8,669.174,675.03,680.887
XS GIS Cut Line= 3
     1711282.128      330257.720     1710855.558      329996.324
     1710434.075      329724.207
#Sta/Elev= 30
       0 1132.90    53.5 1123.35    95.4 1112.86   179.6 1089.13   261.5 1061.04
   293.5 1044.04   318.7 1039.87   370.5 1022.33   382.9 1018.85   389.8 1017.86
   439.3 1015.11   493.5 1015.44   507.2 1012.73   528.3 1006.98   534.4 1005.30
   543.3 1006.36   581.4 1009.18   624.9 1009.82   735.0 1014.65   852.7 1017.64
   853.5 1018.05   867.7 1035.91   869.3 1039.19   871.8 1042.84   881.8 1054.72
   886.5 1056.22   895.9 1063.82   903.7 1068.74   912.2 1071.24  1002.0 1079.61
#Mann= 3 , 0 , 0
       0     0.1       0   528.3   0.045       0   543.3     0.1       0
Bank Sta=   528.3,   543.3
Exp/Cntr=0.3,0.1

Type RM Length L Ch R = 1 ,25855.8,238.075,237.163,236.251
XS GIS Cut Line= 3
     1711630.738      329882.565     1711292.931      329513.260
     1710955.124      329143.954
#Sta/Elev= 30
       0 1086.60    34.7 1079.14   130.6 1051.40   160.3 1047.83   170.4 1047.26
   180.3 1045.33   233.2 1032.52   257.3 1028.74   350.8 1017.10   412.9 1012.66
   499.3 1008.37   530.4 1007.71   558.2 1003.97   563.5 1003.30   573.2 1004.42
   577.2 1004.84   589.7 1009.25   632.8 1022.41   651.8 1026.75   740.9 1031.77
   871.3 1037.48   873.8 1039.42   879.7 1042.48   888.1 1055.81   904.9 1092.44
   907.4 1096.94   913.3 1106.94   921.7 1115.26   985.2 1144.52  1001.0 1150.46
#Mann= 3 , 0 , 0
       0     0.1       0   558.2   0.045       0   573.2     0.1       0
Bank Sta=   558.2,   573.2
Exp/Cntr=0.3,0.1

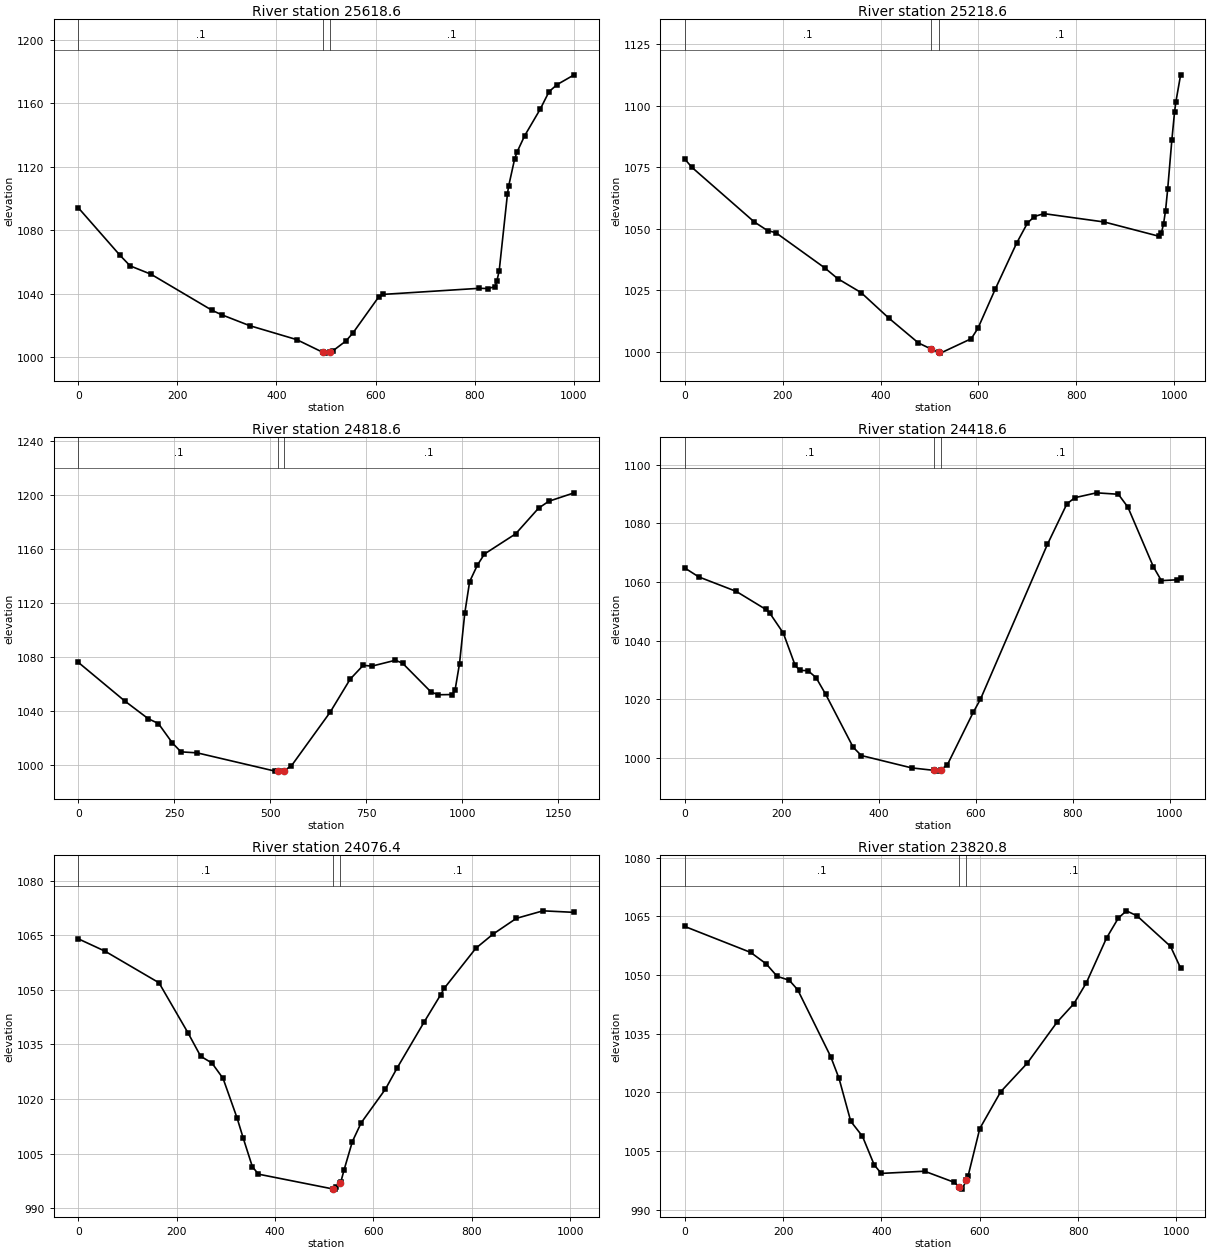
Type RM Length L Ch R = 1 ,25618.6,393.922,400,401.87
XS GIS Cut Line= 3
     1711776.049      329660.263     1711423.568      329304.936
     1711071.087      328949.609
#Sta/Elev= 30
       0 1094.26    84.1 1064.35   104.6 1057.69   146.8 1052.42   270.3 1029.65
   289.9 1026.85   345.8 1020.06   440.8 1011.27     493 1003.35   497.0 1002.75
     508 1003.63   514.3 1004.30   540.3 1010.41   554.4 1015.44   606.1 1038.00
   614.5 1039.72   809.7 1043.57   827.3 1043.42   841.2 1044.62   844.7 1047.86
   849.6 1054.43   866.4 1103.17   868.6 1107.71   880.8 1124.98   885.5 1129.25
   901.1 1139.66   932.2 1156.22   950.3 1167.39   966.2 1171.78  1001.0 1178.00
#Mann= 3 , 0 , 0
       0     0.1       0     493   0.045       0     508     0.1       0
Bank Sta=     493,     508
Exp/Cntr=0.3,0.1

Type RM Length L Ch R = 1 ,25218.6,397.292,400,407.744
XS GIS Cut Line= 3
     1711966.893      329479.538     1711716.436      329033.786
     1711393.763      328649.424
#Sta/Elev= 30
       0 1078.28    14.3 1074.96   142.1 1052.71   169.1 1049.22   186.0 1048.37
   286.1 1034.04   312.2 1029.72   360.2 1024.03   416.6 1013.70   477.4 1003.56
   503.8 1001.05   518.8  999.76   522.4  999.43   585.3 1005.29   599.0 1009.54
   634.3 1025.42   677.8 1044.04   700.1 1052.27   714.3 1054.94   733.7 1056.11
   857.2 1052.71   967.9 1046.97   973.7 1048.16   978.2 1051.95   982.3 1057.37
   986.7 1066.16   995.1 1085.85  1000.7 1097.42  1003.5 1101.66  1013.1 1112.51
#Mann= 3 , 0 , 0
       0     0.1       0   503.8   0.045       0   518.8     0.1       0
Bank Sta=   503.8,   518.8
Exp/Cntr=0.3,0.1

Type RM Length L Ch R = 1 ,24818.6,406.122,400,393.578
XS GIS Cut Line= 3
     1712216.475      329299.481     1712020.407      328808.772
     1711763.128      328089.886
#Sta/Elev= 30
       0 1076.04   120.3 1047.61   182.1 1034.34   208.6 1030.78   244.9 1016.45
   267.4 1009.80   309.7 1009.05   512.5  995.53   520.9  995.65   535.9  995.85
   555.2  999.43   656.1 1039.12   708.4 1063.65   742.2 1073.83   765.4 1073.29
   826.1 1077.61   844.7 1075.47   918.9 1054.15   937.6 1052.06   974.7 1052.23
   981.8 1055.73   993.3 1075.18  1007.0 1112.52  1019.6 1135.79  1039.7 1147.96
  1058.3 1156.28  1139.5 1171.19  1199.1 1190.15  1225.6 1195.28  1292.0 1201.56
#Mann= 3 , 0 , 0
       0     0.1       0   520.9   0.045       0   535.9     0.1       0
Bank Sta=   520.9,   535.9
Exp/Cntr=0.3,0.1

Type RM Length L Ch R = 1 ,24418.6,327.115,342.203,357.861
XS GIS Cut Line= 3
     1712660.024      329070.993     1712341.297      328658.736
     1712044.382      328254.343
#Sta/Elev= 30
       0 1064.74    28.7 1061.71   106.2 1056.76   166.8 1050.66   175.4 1049.33
   203.2 1042.55   227.6 1031.56   237.1 1029.84   254.1 1029.74   270.7 1027.39
   290.8 1021.63   347.2 1003.67   364.1 1000.82   468.0  996.60   513.6  995.77
   524.9  995.50   528.6  995.97   541.9  997.75   595.1 1015.58   609.8 1019.97
   747.9 1072.75   788.2 1086.60   804.7 1088.71   849.3 1090.36   894.3 1089.87
   914.0 1085.49   966.7 1065.11   983.1 1060.43  1015.4 1060.72  1022.8 1061.22
#Mann= 3 , 0 , 0
       0     0.1       0   513.6   0.045       0   528.6     0.1       0
Bank Sta=   513.6,   528.6
Exp/Cntr=0.3,0.1

Type RM Length L Ch R = 1 ,24076.4,258.033,255.596,252.062
XS GIS Cut Line= 3
     1712713.229      329040.921     1712640.638      328536.786
     1712653.890      328038.021
#Sta/Elev= 30
       0 1064.00    54.0 1060.63   164.0 1051.94   222.8 1038.24   248.8 1031.76
   271.6 1029.92   294.3 1025.69   322.9 1014.79   335.2 1009.34   353.9 1001.45
   366.2  999.40   517.9  995.33   519.2  995.29   521.7  995.38   523.5  995.76
   532.9  997.04   533.6  997.15   540.5 1000.62   557.3 1008.36   575.1 1013.48
   624.5 1022.74   648.5 1028.60   703.6 1041.25   736.5 1048.57   743.8 1050.37
   808.4 1061.42   843.5 1065.31   890.7 1069.62   944.9 1071.69  1008.3 1071.27
#Mann= 3 , 0 , 0
       0     0.1       0   517.9   0.045       0   532.9     0.1       0
Bank Sta=   517.9,   532.9
Exp/Cntr=0.3,0.1

Type RM Length L Ch R = 1 ,23820.8,611.746,602.2,597.333
XS GIS Cut Line= 3
     1712871.926      329074.921     1712903.913      328577.033
     1712837.967      328071.834
#Sta/Elev= 30
       0 1062.43   134.0 1055.79   165.6 1052.86   187.8 1049.68   212.4 1048.68
   229.6 1046.24   296.7 1029.15   313.7 1023.56   337.5 1012.60   361.3 1008.77
   385.1 1001.49   399.4  999.27   487.7  999.83   548.0  996.99   557.8  995.87
   563.9  995.25   572.8  997.52   575.9  998.48   599.9 1010.73   642.5 1020.16
   696.2 1027.42   757.2 1037.97   791.4 1042.69   816.8 1048.05   857.7 1059.47
   881.8 1064.59   898.2 1066.43   919.7 1065.15   987.9 1057.33  1008.4 1051.78
#Mann= 3 , 0 , 0
       0     0.1       0   557.8   0.045       0   572.8     0.1       0
Bank Sta=   557.8,   572.8
Exp/Cntr=0.3,0.1

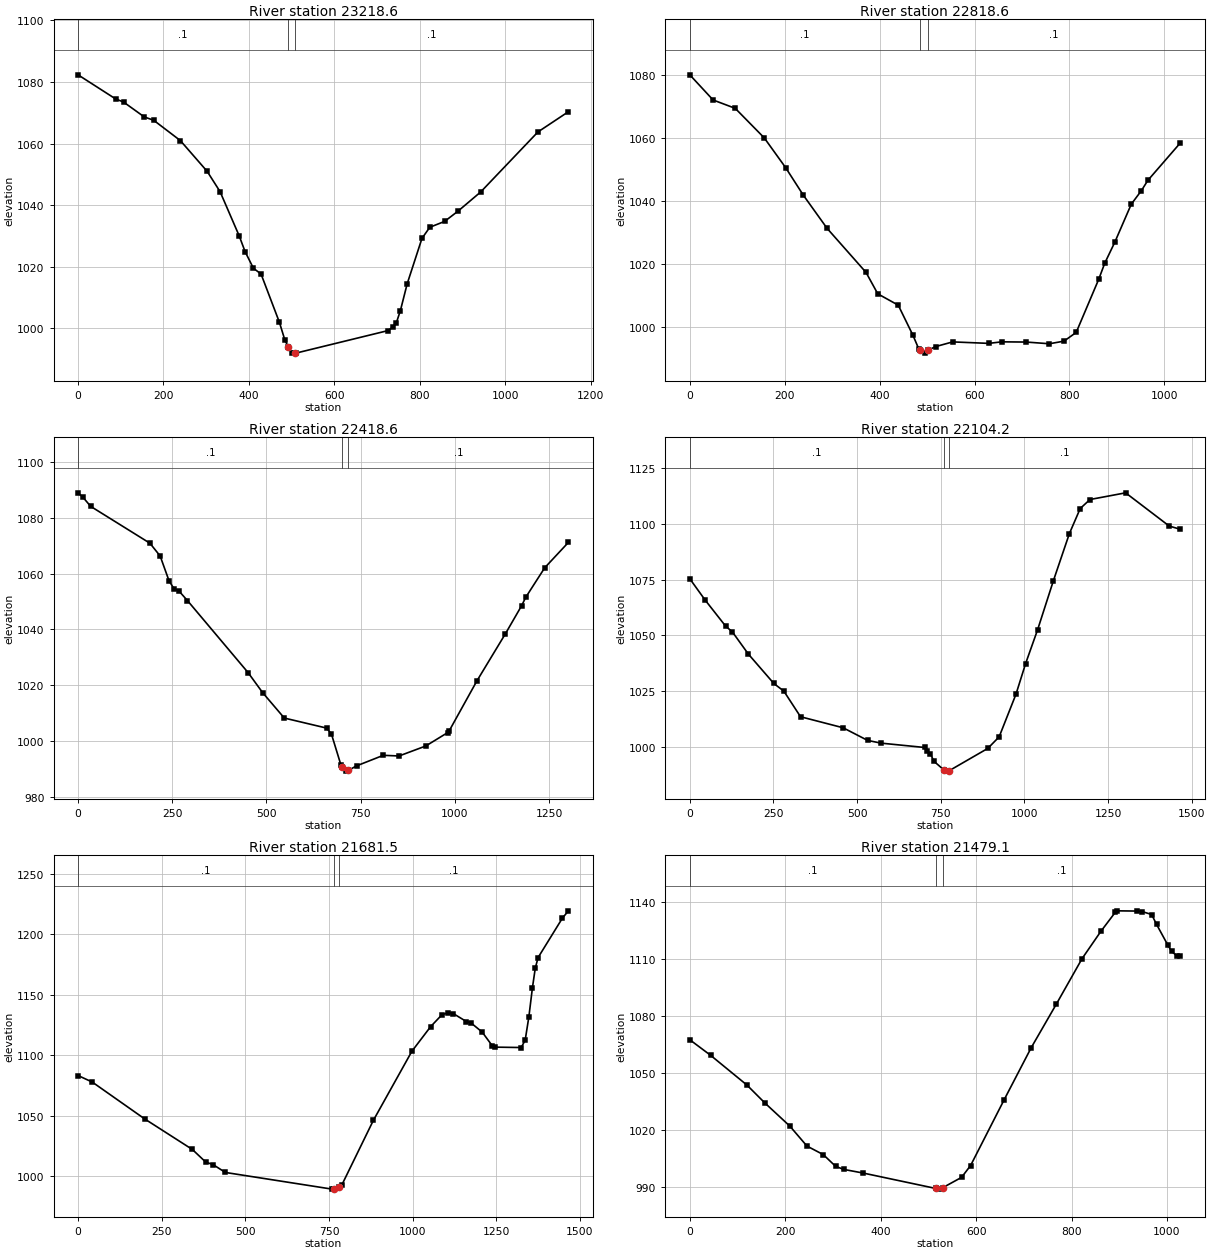
Type RM Length L Ch R = 1 ,23218.6,410.786,400,387.278
XS GIS Cut Line= 3
     1713717.730      328927.801     1713454.791      328502.859
     1713232.764      327893.449
#Sta/Elev= 30
       0 1082.32    87.8 1074.50   106.7 1073.46   155.1 1068.63   177.0 1067.56
   239.6 1060.94   302.3 1050.95   332.5 1044.36   377.3 1029.98   391.2 1024.83
   410.6 1019.46   428.5 1017.58   471.5 1001.88   484.5  996.01   492.2  993.98
   500.7  991.96   507.2  991.90   510.0  991.87   725.7  999.19   737.2 1000.39
   745.1 1001.65   754.8 1005.70   770.7 1014.41   805.3 1029.17   823.7 1032.78
   858.3 1034.68   889.4 1037.98   942.9 1044.26  1076.9 1063.76  1148.3 1070.34
#Mann= 3 , 0 , 0
       0     0.1       0   492.2   0.045       0   507.2     0.1       0
Bank Sta=   492.2,   507.2
Exp/Cntr=0.3,0.1

Type RM Length L Ch R = 1 ,22818.6,403.8,400,390.785
XS GIS Cut Line= 3
     1714215.265      328559.397     1713795.407      328299.907
     1713373.972      327962.693
#Sta/Elev= 30
       0 1080.04    49.1 1072.04    95.7 1069.39   156.9 1059.99   202.0 1050.52
   239.2 1041.78   289.4 1031.21   371.3 1017.23   396.1 1010.41   439.2 1006.81
   470.3  997.20   482.4  992.92   486.1  992.45   495.3  991.56   501.1  992.44
   518.1  993.64   553.9  995.13   629.9  994.66   657.3  995.15   708.9  995.08
   757.7  994.54   788.5  995.37   814.2  998.15   861.7 1015.06   874.4 1020.17
   895.6 1026.85   930.3 1038.93   951.4 1043.19   965.3 1046.51  1033.3 1058.34
#Mann= 3 , 0 , 0
       0     0.1       0   486.1   0.045       0   501.1     0.1       0
Bank Sta=   486.1,   501.1
Exp/Cntr=0.3,0.1

Type RM Length L Ch R = 1 ,22418.6,294.337,314.457,337.861
XS GIS Cut Line= 3
     1714607.820      328199.017     1713943.741      327949.714
     1713370.997      327798.869
#Sta/Elev= 30
       0 1089.02    13.2 1087.39    33.5 1084.16   190.7 1070.94   217.9 1066.34
   241.4 1057.47   254.5 1054.61   266.8 1053.94   290.3 1050.35   451.1 1024.53
   489.8 1017.33   547.4 1008.19   659.9 1004.58   672.6 1002.42   698.0  991.20
   701.8  990.62   710.6  989.14   716.8  989.37   739.1  991.02   810.1  994.81
   852.0  994.58   922.9  998.16   980.7 1002.94   984.9 1003.55  1058.6 1021.52
  1134.5 1038.49  1177.2 1048.49  1188.5 1051.57  1238.6 1062.12  1301.6 1071.25
#Mann= 3 , 0 , 0
       0     0.1       0   701.8   0.045       0   716.8     0.1       0
Bank Sta=   701.8,   716.8
Exp/Cntr=0.3,0.1

Type RM Length L Ch R = 1 ,22104.2,432.106,422.703,413.307
XS GIS Cut Line= 3
     1714554.175      328046.668     1713946.414      327670.612
     1713308.235      327274.604
#Sta/Elev= 30
       0 1075.34    45.7 1065.83   106.9 1054.16   127.4 1051.52   175.1 1041.60
   251.2 1028.45   281.2 1025.01   331.0 1013.56   458.1 1008.63   531.6 1002.96
   571.7 1001.74   702.4  999.79   708.0  998.19   719.3  996.99   729.3  993.67
     760  989.69   768.8  989.21     775  989.37   890.7  999.38   924.7 1004.57
   975.1 1023.70  1003.7 1037.35  1039.8 1052.59  1086.9 1074.50  1134.6 1095.56
  1167.0 1106.79  1196.1 1110.81  1302.7 1113.81  1433.1 1098.93  1465.8 1097.51
#Mann= 3 , 0 , 0
       0     0.1       0     760   0.045       0     775     0.1       0
Bank Sta=     760,     775
Exp/Cntr=0.3,0.1

Type RM Length L Ch R = 1 ,21681.5,199.475,202.362,204.509
XS GIS Cut Line= 3
     1714600.544      328017.132     1714156.743      327456.924
     1713691.116      326867.614
#Sta/Elev= 30
       0 1083.15    42.3 1077.78   199.7 1047.13   341.6 1021.94   381.9 1011.41
   403.1 1009.48   440.3 1002.90   759.3  989.09   765.9  989.21   780.9  990.51
   787.8  992.17   882.5 1045.94   997.9 1103.29  1054.0 1123.70  1087.7 1133.51
  1107.2 1135.22  1121.6 1134.46  1160.6 1127.89  1175.2 1126.60  1208.1 1119.10
  1237.7 1107.95  1245.6 1106.68  1324.4 1106.35  1336.4 1112.34  1347.5 1131.80
  1358.2 1155.97  1366.7 1172.15  1375.1 1180.88  1448.0 1213.62  1465.8 1219.56
#Mann= 3 , 0 , 0
       0     0.1       0   765.9   0.045       0   780.9     0.1       0
Bank Sta=   765.9,   780.9
Exp/Cntr=0.3,0.1

Type RM Length L Ch R = 1 ,21479.1,258.7,260.478,259.432
XS GIS Cut Line= 3
     1714606.524      327820.266     1714313.053      327371.089
     1714039.886      326962.678
#Sta/Elev= 30
       0 1067.47    43.5 1059.32   119.8 1043.67   157.1 1034.34   209.8 1022.10
   245.5 1011.67   279.8 1007.17   305.5 1001.04   322.2  999.43   363.3  997.50
     515  989.44   522.1  989.06     530  989.80   569.5  995.23   588.5 1001.46
   658.9 1036.03   715.5 1063.31   768.3 1086.24   822.2 1110.10   861.4 1124.34
   891.6 1134.34   894.7 1135.14   938.1 1135.01   948.7 1134.69   967.9 1133.21
   978.2 1128.01  1001.8 1117.17  1009.7 1113.83  1021.9 1111.27  1027.7 1111.21
#Mann= 3 , 0 , 0
       0     0.1       0     515   0.045       0     530     0.1       0
Bank Sta=     515,     530
Exp/Cntr=0.3,0.1

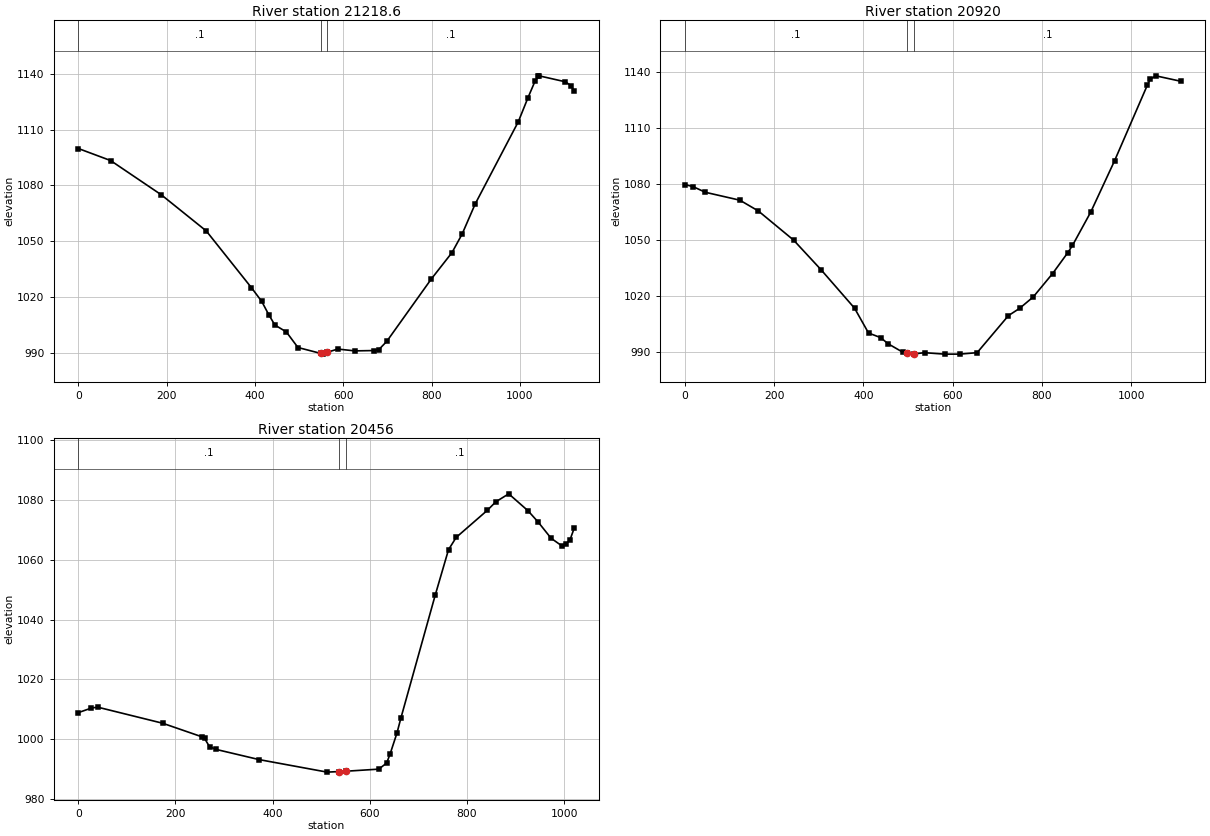
Type RM Length L Ch R = 1 ,21218.6,294.957,298.636,296.477
XS GIS Cut Line= 3
     1714847.909      327820.695     1714576.679      327334.518
     1714246.990      326874.306
#Sta/Elev= 30
       0 1099.81    73.0 1093.35   187.9 1074.93   289.7 1055.51   392.1 1024.98
   415.2 1017.67   431.3 1010.47   445.0 1004.96   471.1 1001.22   497.3  992.86
   549.2  989.67   553.7  989.30   564.2  990.31   587.3  992.03   626.4  991.04
   670.3  991.23   680.2  991.67   698.4  996.14   799.2 1029.65   846.1 1043.86
   869.1 1053.83   898.6 1069.97   996.3 1114.20  1018.4 1127.22  1034.5 1136.17
  1041.8 1138.53  1043.4 1138.88  1102.9 1135.67  1115.6 1133.58  1122.8 1130.80
#Mann= 3 , 0 , 0
       0     0.1       0   549.2   0.045       0   564.2     0.1       0
Bank Sta=   549.2,   564.2
Exp/Cntr=0.3,0.1

Type RM Length L Ch R = 1 ,20920,474.474,464.017,462.332
XS GIS Cut Line= 3
     1715066.171      327595.157     1714796.981      327180.458
     1714310.961      326802.155
#Sta/Elev= 30
       0 1079.86    18.6 1078.72    45.9 1075.70   123.3 1071.46   164.6 1065.71
   243.5 1050.13   304.9 1034.30   380.2 1013.64   411.4 1000.38   438.9  997.87
   454.9  994.67   487.5  990.18   498.6  989.63   513.6  989.25   537.2  989.83
   581.6  989.07   615.5  989.07   654.6  989.85   724.7 1009.68   749.7 1013.57
   780.2 1019.66   823.7 1032.22   857.8 1043.43   868.1 1047.23   909.0 1065.09
   962.3 1092.53  1035.6 1132.94  1042.4 1136.24  1054.7 1138.03  1110.3 1135.14
#Mann= 3 , 0 , 0
       0     0.1       0   498.6   0.045       0   513.6     0.1       0
Bank Sta=   498.6,   513.6
Exp/Cntr=0.3,0.1

Type RM Length L Ch R = 1 ,20456,434.163,437.347,434.129
XS GIS Cut Line= 3
     1715328.595      327105.926     1714934.566      326778.452
     1714565.394      326428.826
#Sta/Elev= 30
       0 1008.89    27.0 1010.43    39.8 1010.72   173.4 1005.35   255.2 1000.76
   259.8 1000.28   270.1  997.51   284.3  996.56   372.5  993.17   512.3  988.99
   536.5  989.18   551.5  989.30   618.5  989.99   634.7  992.02   641.8  995.02
   656.1 1002.12   664.1 1007.08   734.9 1048.27   762.1 1063.38   777.9 1067.49
   842.2 1076.58   859.5 1079.40   886.1 1082.07   925.7 1076.42   946.6 1072.65
   973.2 1067.23   994.8 1064.74  1003.7 1065.30  1012.1 1066.61  1020.8 1070.55
#Mann= 3 , 0 , 0
       0     0.1       0   536.5   0.045       0   551.5     0.1       0
Bank Sta=   536.5,   551.5
Exp/Cntr=0.3,0.1