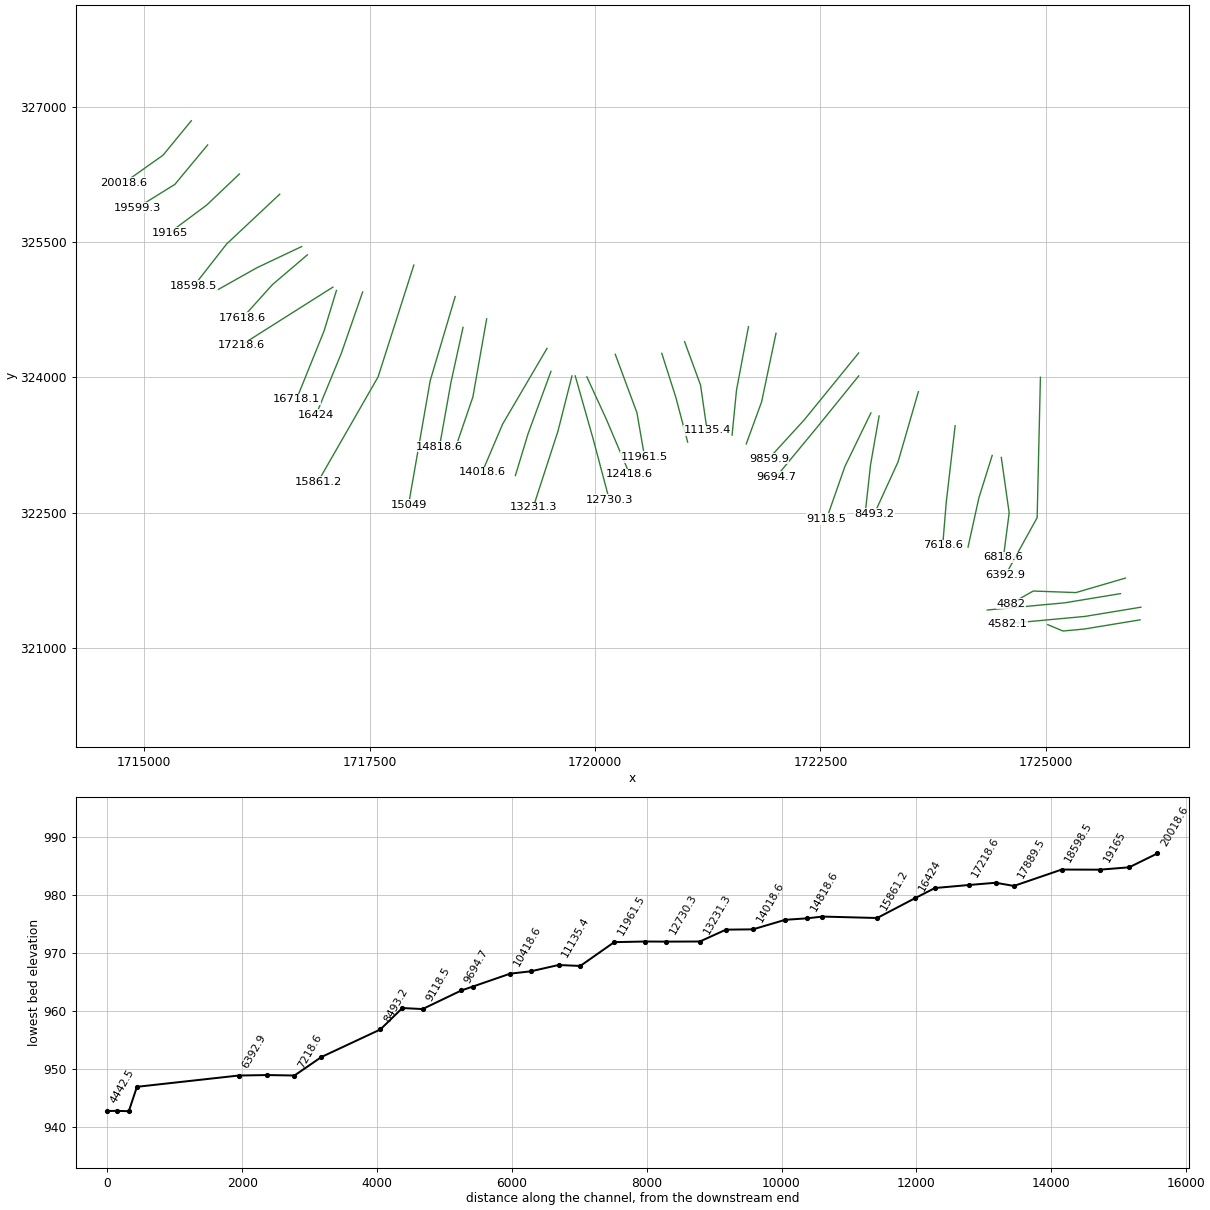
HEC-RAS study JonesCr.prj: JonesCr

--- JonesCr.g01 (geometry) --- (continued)

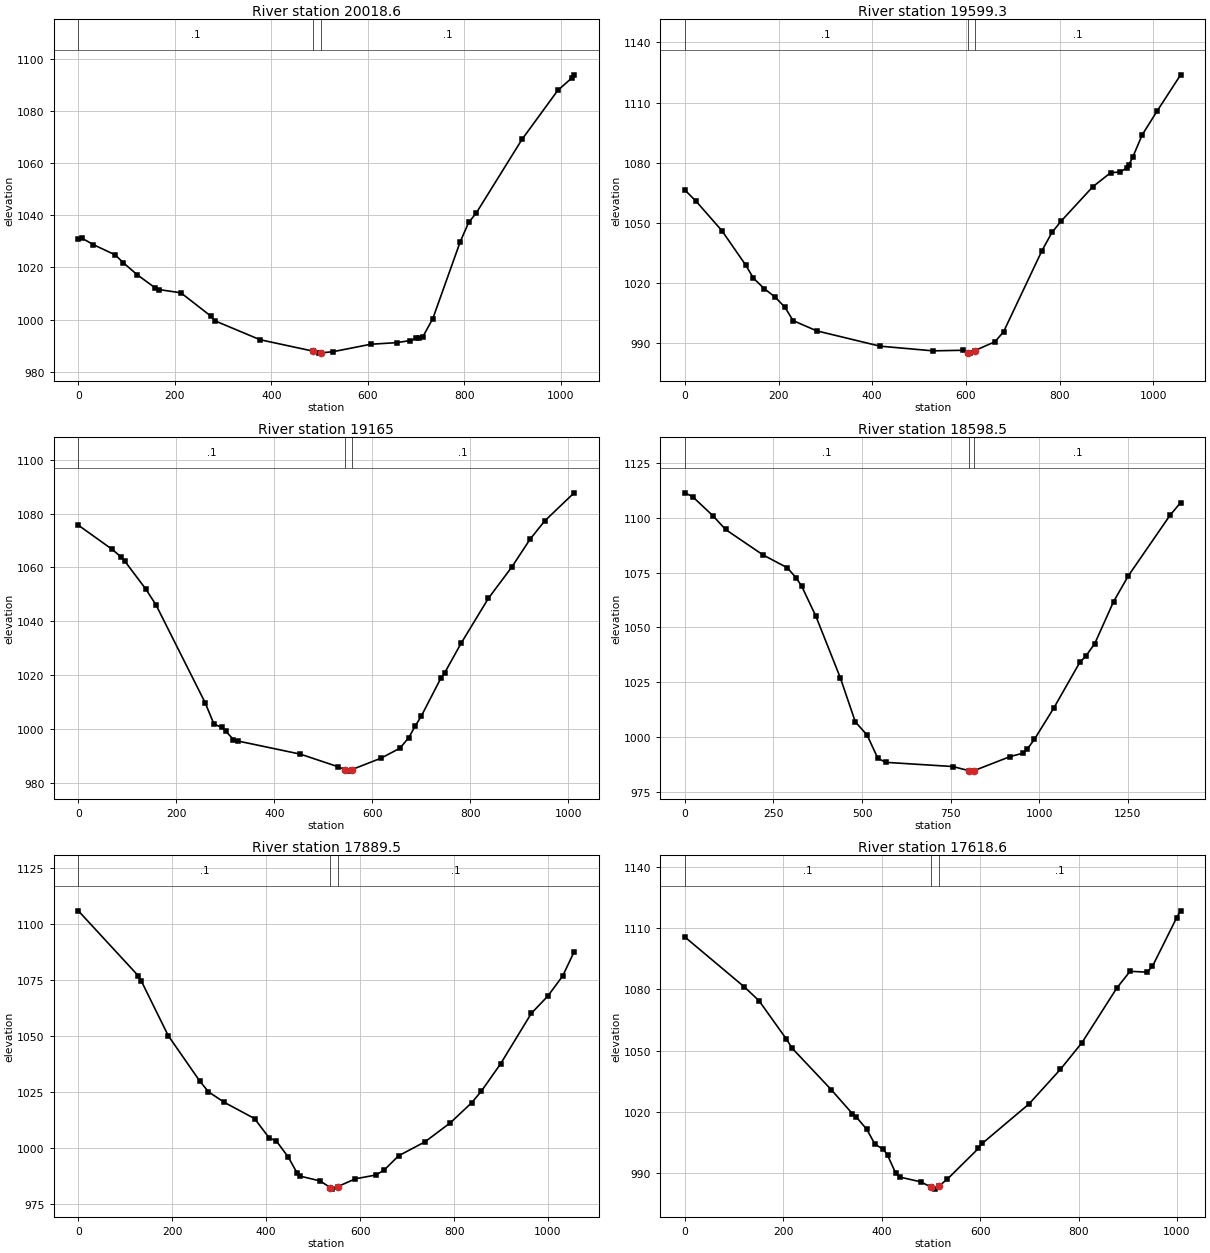
Type RM Length L Ch R = 1 ,20018.6,427.164,419.287,417.575
XS GIS Cut Line= 3
     1715523.741      326845.950     1715209.938      326463.579
     1714775.215      326155.608
#Sta/Elev= 30
       0 1030.95     7.3 1031.22    31.3 1028.71    76.6 1024.79    92.6 1021.89
   121.7 1017.25   158.7 1012.24   167.2 1011.52   212.5 1010.29   273.9 1001.46
   282.6  999.60   376.4  992.33   487.2  987.92   497.7  987.19   502.2  987.28
   527.8  987.74   606.0  990.59   660.1  991.21   687.6  992.01   699.8  992.83
   706.9  992.96   713.8  993.43   734.6 1000.44   791.5 1029.93   808.9 1037.26
   824.1 1040.71   919.3 1069.02   993.4 1087.77  1022.9 1092.61  1027.4 1093.75
#Mann= 3 , 0 , 0
       0     0.1       0   487.2   0.045       0   502.2     0.1       0
Bank Sta=   487.2,   502.2
Exp/Cntr=0.3,0.1

Type RM Length L Ch R = 1 ,19599.3,433.746,434.369,435.23
XS GIS Cut Line= 3
     1715704.405      326577.220     1715340.904      326139.694
     1714925.087      325881.509
#Sta/Elev= 30
       0 1066.32    23.9 1060.72    79.2 1045.96   129.6 1028.92   146.6 1022.21
   169.3 1017.06   192.0 1012.94   213.7 1007.74   231.0 1001.06   281.5  995.92
   416.4  988.28   529.8  985.93   593.7  986.22   603.6  985.07   607.7  984.79
   618.6  986.01   662.0  990.48   680.3  995.42   762.5 1036.06   783.7 1045.10
   803.4 1050.78   870.7 1067.89   908.9 1074.92   929.2 1075.30   943.1 1077.26
   947.5 1078.68   956.2 1082.74   976.2 1093.82  1007.9 1105.65  1058.3 1123.84
#Mann= 3 , 0 , 0
       0     0.1       0   603.6   0.045       0   618.6     0.1       0
Bank Sta=   603.6,   618.6
Exp/Cntr=0.3,0.1

Type RM Length L Ch R = 1 ,19165,562.085,566.474,572.702
XS GIS Cut Line= 3
     1716056.716      326255.169     1715693.292      325909.872
     1715283.179      325605.364
#Sta/Elev= 30
       0 1075.67    67.9 1066.84    87.4 1063.88    94.9 1062.29   137.9 1051.89
   158.5 1046.07   258.6 1009.82   276.6 1001.90   292.1 1000.61   300.8  999.19
   316.5  996.09   325.2  995.57   453.2  990.68   530.7  985.96   543.2  984.96
   550.5  984.38   558.2  984.96   617.6  989.19   656.2  992.90   674.1  996.80
   687.4 1001.15   699.3 1004.66   739.5 1018.82   747.7 1020.97   781.2 1031.91
   836.6 1048.51   884.5 1060.16   921.7 1070.47   951.8 1077.30  1011.6 1087.68
#Mann= 3 , 0 , 0
       0     0.1       0   543.2   0.045       0   558.2     0.1       0
Bank Sta=   543.2,   558.2
Exp/Cntr=0.3,0.1

Type RM Length L Ch R = 1 ,18598.5,713.594,708.979,700.134
XS GIS Cut Line= 3
     1716503.582      326030.941     1715914.273      325478.008
     1715550.501      325012.381
#Sta/Elev= 30
       0 1111.36    21.9 1109.63    79.0 1100.96   115.0 1094.64   221.0 1083.00
   289.1 1077.19   313.5 1072.71   329.4 1068.90   369.8 1055.09   438.7 1027.03
   481.1 1006.89   514.5 1000.81   544.5  990.31   566.3  988.42   756.7  986.49
   801.2  984.61   812.9  984.40   816.2  984.63   918.0  991.04   955.3  992.63
   966.8  994.57   986.3  998.88  1041.1 1013.17  1114.6 1034.04  1131.3 1036.83
  1156.7 1042.59  1209.8 1061.72  1251.9 1073.62  1368.8 1101.04  1399.0 1106.93
#Mann= 3 , 0 , 0
       0     0.1       0   801.2   0.045       0   816.2     0.1       0
Bank Sta=   801.2,   816.2
Exp/Cntr=0.3,0.1

Type RM Length L Ch R = 1 ,17889.5,265.256,270.89,277.785
XS GIS Cut Line= 3
     1716746.652      325450.261     1716252.066      325216.093
     1715808.797      324966.882
#Sta/Elev= 30
       0 1106.04   127.1 1077.11   133.8 1074.77   191.5 1050.18   258.6 1029.89
   277.1 1025.09   310.7 1020.39   375.1 1013.14   406.0 1004.58   421.9 1003.01
   447.2  995.85   465.9  988.73   472.9  987.35   514.8  985.24   536.9  982.19
   541.0  981.57   551.9  982.67   590.0  986.19   633.3  987.87   650.8  990.03
   681.9  996.48   738.0 1002.72   792.3 1011.27   837.6 1020.23   857.9 1025.33
   899.0 1037.59   964.6 1060.22   999.5 1067.88  1031.1 1076.86  1055.7 1087.73
#Mann= 3 , 0 , 0
       0     0.1       0   536.9   0.045       0   551.9     0.1       0
Bank Sta=   536.9,   551.9
Exp/Cntr=0.3,0.1

Type RM Length L Ch R = 1 ,17618.6,402.839,400,394.188
XS GIS Cut Line= 3
     1716810.515      325358.417     1716423.418      325028.751
     1716089.432      324657.873
#Sta/Elev= 30
       0 1105.65   120.6 1081.25   150.8 1074.42   205.9 1055.80   218.1 1051.15
   297.3 1030.91   340.3 1019.14   348.3 1017.51   369.7 1011.41   386.6 1004.07
   403.4 1001.65   411.9  998.79   428.7  989.85   437.1  988.01   479.2  985.71
     501  983.07   508.5  982.12     516  983.53   533.5  987.01   596.5 1002.03
   604.6 1004.55   699.5 1023.86   763.2 1040.79   807.1 1053.89   878.0 1080.68
   904.8 1088.83   939.1 1088.40   950.1 1091.18   999.3 1114.99  1007.5 1118.45
#Mann= 3 , 0 , 0
       0     0.1       0     501   0.045       0     516     0.1       0
Bank Sta=     501,     516
Exp/Cntr=0.3,0.1

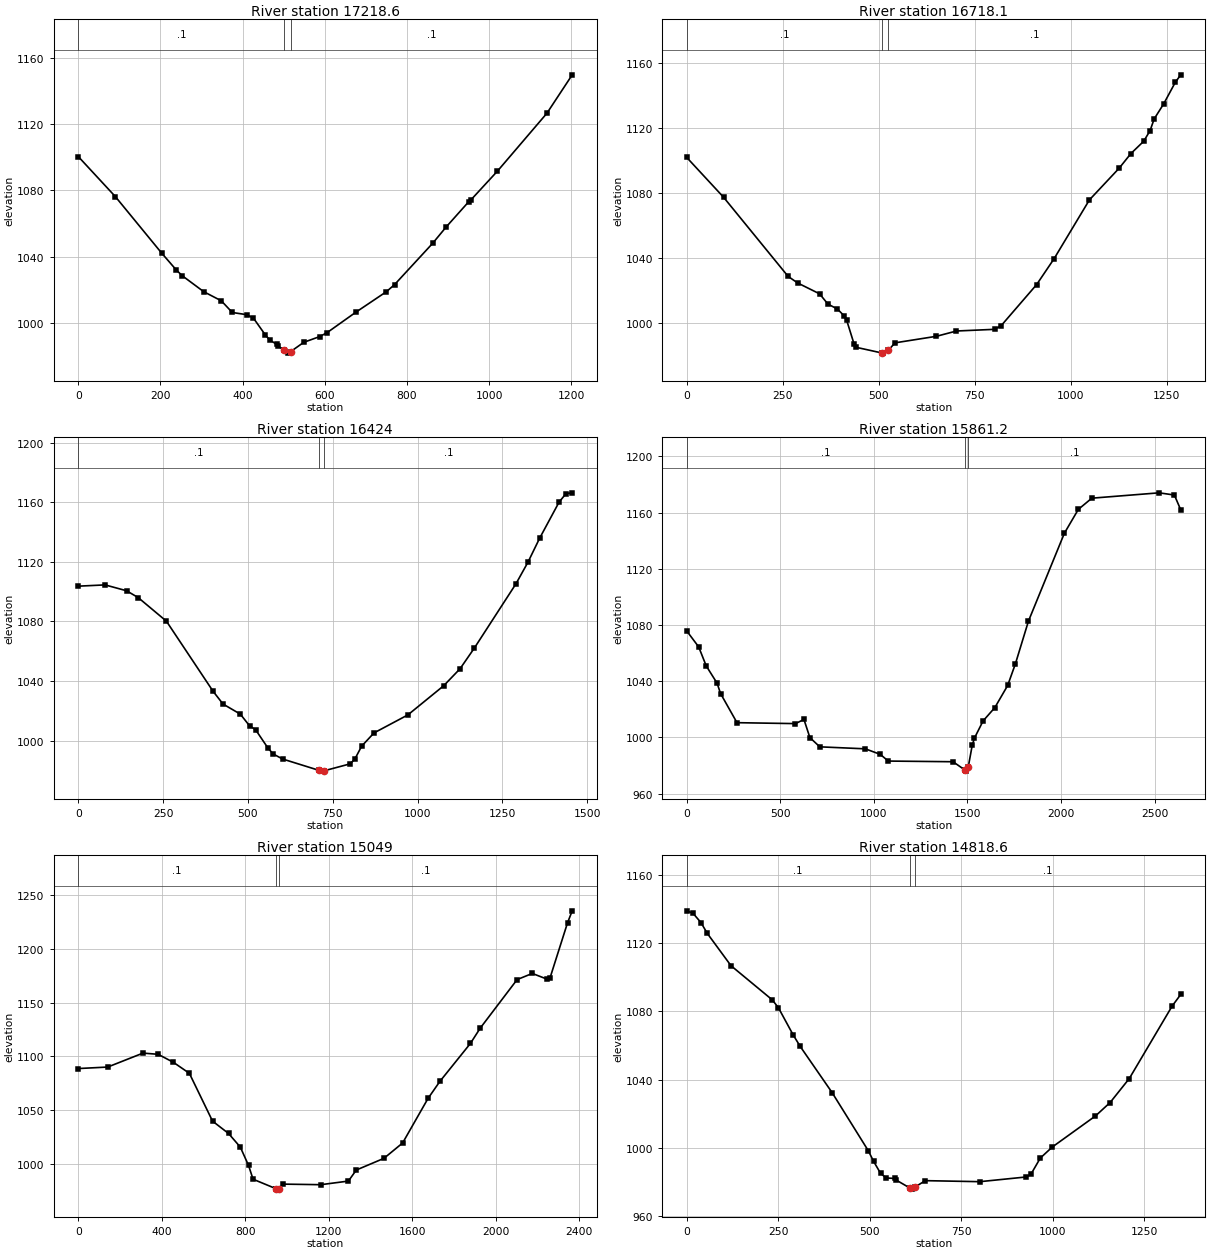
Type RM Length L Ch R = 1 ,17218.6,486.456,500.497,514.517
XS GIS Cut Line= 3
     1717093.355      325000.336     1716662.816      324728.221
     1716077.456      324357.593
#Sta/Elev= 30
       0 1100.53    90.2 1076.34   203.1 1042.15   238.3 1032.07   252.7 1028.57
   305.3 1018.87   348.2 1013.34   374.9 1006.29   409.9 1004.97   426.5 1002.84
   455.3  992.74   466.1  989.67   483.0  987.03   486.8  985.96   501.8  983.35
   511.1  981.73   516.8  982.62   548.9  988.27   587.7  991.73   605.9  994.15
   674.8 1006.31   750.0 1018.86   769.8 1023.12   862.4 1048.04   895.2 1057.89
   950.3 1073.21   955.5 1074.28  1020.3 1091.73  1140.7 1126.70  1202.2 1149.89
#Mann= 3 , 0 , 0
       0     0.1       0   501.8   0.045       0   516.8     0.1       0
Bank Sta=   501.8,   516.8
Exp/Cntr=0.3,0.1

Type RM Length L Ch R = 1 ,16718.1,292.494,294.095,295.073
XS GIS Cut Line= 3
     1717132.732      324963.365     1716995.207      324514.005
     1716689.639      323757.360
#Sta/Elev= 30
       0 1101.84    95.7 1077.36   264.0 1028.50   288.8 1024.46   345.8 1017.77
   367.6 1011.43   392.1 1008.44   410.5 1004.02   416.1 1001.68   435.3  987.08
   440.6  984.82   509.5  981.23   510.1  981.21   524.5  982.84   542.1  987.55
   650.1  991.59   702.2  994.85   801.3  995.88   818.4  998.10   910.8 1023.44
   956.4 1039.44  1048.3 1075.68  1125.7 1095.21  1156.2 1104.21  1189.7 1111.84
  1206.3 1118.41  1216.9 1125.61  1241.6 1134.85  1271.8 1148.12  1286.0 1152.78
#Mann= 3 , 0 , 0
       0     0.1       0   509.5   0.045       0   524.5     0.1       0
Bank Sta=   509.5,   524.5
Exp/Cntr=0.3,0.1

Type RM Length L Ch R = 1 ,16424,566.576,562.795,559.285
XS GIS Cut Line= 3
     1717423.409      324946.902     1717186.831      324266.383
     1716906.854      323586.398
#Sta/Elev= 30
       0 1103.65    79.1 1104.50   142.5 1100.56   176.9 1095.94   259.8 1080.15
   397.4 1033.06   426.7 1024.50   477.6 1017.74   504.8 1009.91   522.7 1007.26
   558.4  995.19   574.1  991.03   602.2  987.60   710.3  979.93   716.9  979.46
   725.3  979.73   800.8  984.31   814.9  987.42   835.2  996.21   871.6 1005.11
   971.6 1017.23  1077.0 1036.79  1125.3 1048.21  1167.4 1062.10  1290.0 1105.24
  1325.2 1119.67  1359.5 1135.72  1417.3 1160.18  1437.7 1165.83  1455.8 1166.32
#Mann= 3 , 0 , 0
       0     0.1       0   710.3   0.045       0   725.3     0.1       0
Bank Sta=   710.3,   725.3
Exp/Cntr=0.3,0.1

Type RM Length L Ch R = 1 ,15861.2,808.6,812.251,816.848
XS GIS Cut Line= 3
     1717990.892      325245.195     1717594.382      324004.735
     1716928.680      322844.304
#Sta/Elev= 30
       0 1075.74    63.9 1064.39   104.0 1050.92   162.2 1038.56   180.7 1031.24
   268.6 1010.49   581.2 1009.83   626.5 1012.78   658.1  999.90   711.1  993.31
   954.4  991.89  1034.3  987.97  1077.0  983.19  1423.4  982.71  1489.8  976.52
  1492.8  976.03  1504.8  979.16  1525.7  994.33  1537.1  999.38  1584.0 1011.77
  1646.6 1021.21  1715.3 1036.98  1756.8 1052.46  1826.4 1082.78  2018.4 1145.28
  2093.0 1162.24  2165.0 1170.19  2524.9 1174.00  2606.2 1172.43  2640.1 1161.92
#Mann= 3 , 0 , 0
       0     0.1       0  1489.8   0.045       0  1504.8     0.1       0
Bank Sta=  1489.8,  1504.8
Exp/Cntr=0.3,0.1

Type RM Length L Ch R = 1 ,15049,228.699,230.362,232.347
XS GIS Cut Line= 3
     1718449.244      324895.974     1718172.778      323964.720
     1717932.689      322589.664
#Sta/Elev= 30
       0 1088.66   141.0 1090.05   310.5 1103.06   382.7 1101.94   456.2 1094.45
   532.5 1084.23   643.6 1039.67   720.4 1028.13   776.6 1015.48   816.2  998.37
   837.7  985.53     946  976.82   949.5  976.28     961  976.83   982.9  980.95
  1162.0  980.41  1294.7  983.78  1332.4  994.07  1465.0 1004.97  1554.5 1019.28
  1676.4 1060.85  1733.3 1076.73  1879.4 1112.06  1926.4 1126.31  2103.2 1171.57
  2176.0 1177.30  2248.4 1171.85  2260.4 1172.81  2344.8 1224.48  2367.3 1235.66
#Mann= 3 , 0 , 0
       0     0.1       0     946   0.045       0     961     0.1       0
Bank Sta=     946,     961
Exp/Cntr=0.3,0.1

Type RM Length L Ch R = 1 ,14818.6,320.59,321.347,320.125
XS GIS Cut Line= 3
     1718536.549      324554.029     1718404.049      323952.074
     1718274.634      323229.902
#Sta/Elev= 30
       0 1138.82    17.3 1137.35    38.9 1131.93    56.3 1125.57   121.0 1106.70
   233.6 1086.75   250.3 1082.20   290.7 1066.27   310.2 1059.44   397.1 1032.51
   496.1  998.47   510.8  992.18   529.9  985.14   545.3  982.50   568.3  982.22
   573.2  981.18   608.9  976.74   615.0  975.97   623.9  977.20   652.0  980.93
   801.0  980.33   927.0  983.07   940.6  984.64   966.2  994.13   998.8 1000.57
  1117.1 1018.80  1157.1 1026.65  1209.5 1040.70  1326.6 1083.10  1350.0 1089.87
#Mann= 3 , 0 , 0
       0     0.1       0   608.9   0.045       0   623.9     0.1       0
Bank Sta=   608.9,   623.9
Exp/Cntr=0.3,0.1

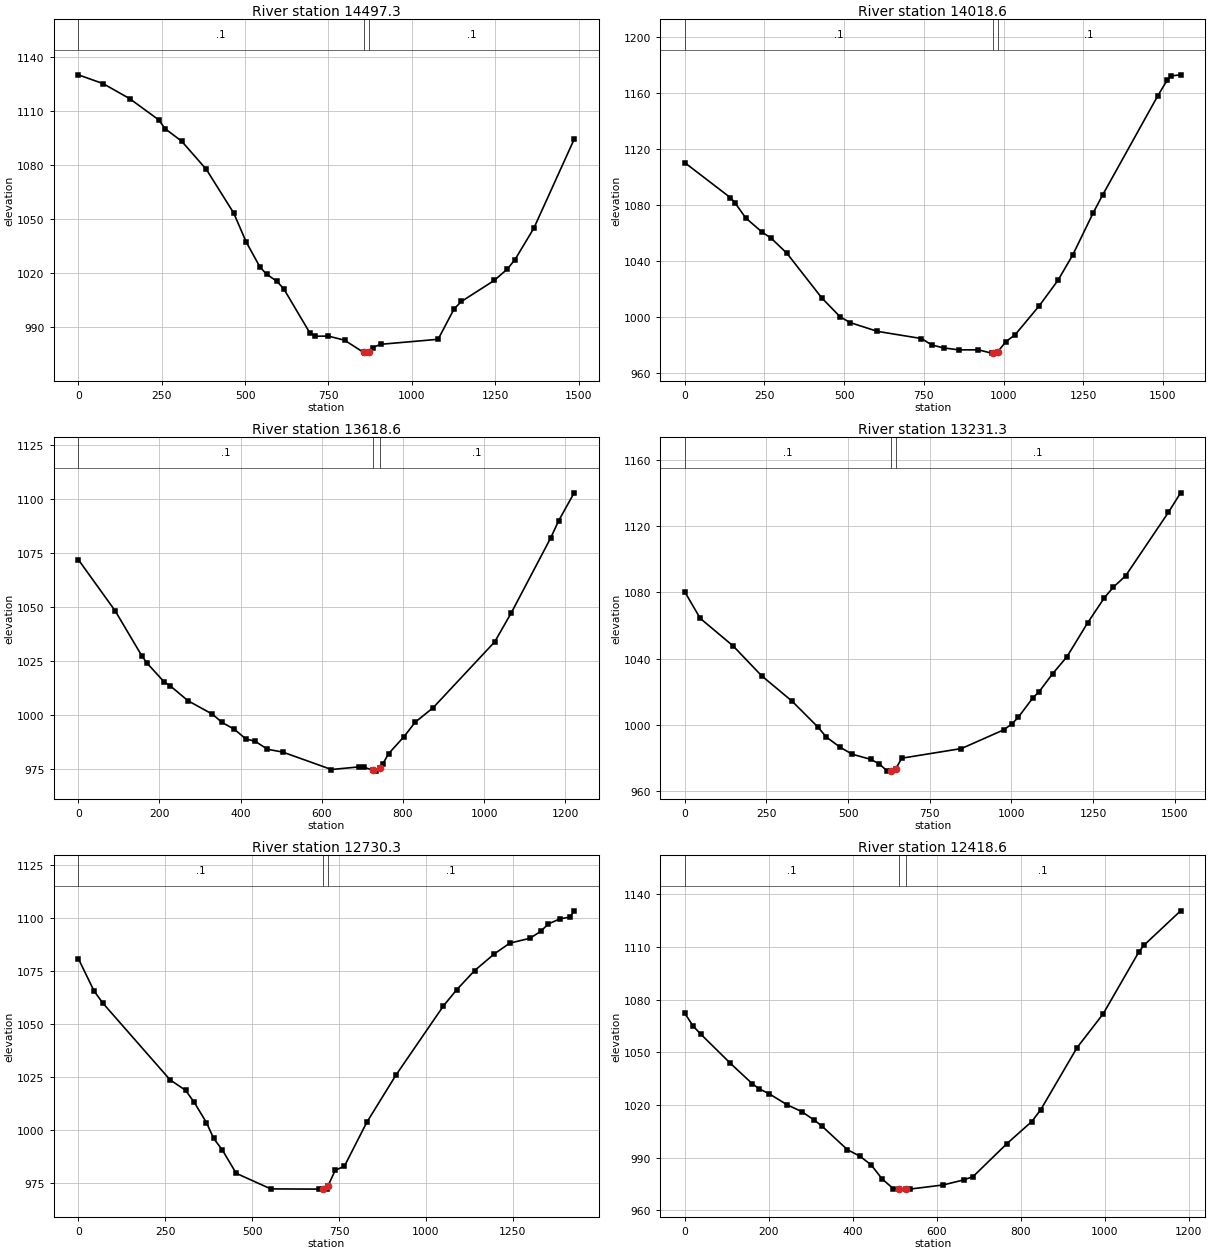
Type RM Length L Ch R = 1 ,14497.3,486.89,478.653,474.612
XS GIS Cut Line= 3
     1718798.465      324648.610     1718645.681      323782.834
     1718449.244      323208.076
#Sta/Elev= 30
       0 1130.05    74.3 1125.17   153.8 1116.85   241.5 1105.01   259.7 1100.24
   309.8 1093.24   383.7 1077.63   465.8 1053.42   503.1 1037.42   544.5 1023.49
   564.6 1019.44   595.4 1015.57   616.2 1011.30   693.9  986.99   710.5  985.08
   749.5  985.17   798.2  982.89   855.7  976.07   858.0  975.72   870.7  976.30
   882.0  978.77   906.3  980.61  1078.7  983.39  1126.7 1000.28  1148.7 1004.37
  1247.1 1016.05  1286.2 1022.32  1309.2 1027.59  1365.6 1044.94  1486.6 1094.32
#Mann= 3 , 0 , 0
       0     0.1       0   855.7   0.045       0   870.7     0.1       0
Bank Sta=   855.7,   870.7
Exp/Cntr=0.3,0.1

Type RM Length L Ch R = 1 ,14018.6,392.213,400,401.119
XS GIS Cut Line= 3
     1719467.804      324321.216     1718975.250      323481.331
     1718747.537      322946.160
#Sta/Elev= 30
       0 1110.29   142.8 1085.32   156.9 1081.75   191.5 1070.65   242.0 1060.74
   271.4 1056.17   320.1 1045.55   430.1 1013.45   487.3 1000.05   518.4  995.94
   604.3  989.63   742.3  984.50   775.5  979.83   812.5  977.79   859.4  976.41
   921.0  976.42   962.1  974.07   966.2  974.16   981.2  974.86  1006.9  982.23
  1036.2  987.23  1112.0 1007.97  1170.3 1026.07  1216.9 1044.27  1281.4 1074.58
  1310.3 1087.03  1483.7 1158.16  1513.6 1169.50  1526.5 1172.38  1555.3 1173.14
#Mann= 3 , 0 , 0
       0     0.1       0   966.2   0.045       0   981.2     0.1       0
Bank Sta=   966.2,   981.2
Exp/Cntr=0.3,0.1

Type RM Length L Ch R = 1 ,13618.6,386.434,387.334,386.498
XS GIS Cut Line= 3
     1719511.456      324066.576     1719258.259      323376.625
     1719116.653      322910.484
#Sta/Elev= 30
       0 1071.94    90.7 1048.25   156.0 1027.55   169.1 1024.06   211.4 1015.33
   225.9 1013.59   270.3 1006.60   330.6 1000.37   354.1  996.57   384.7  993.38
   412.9  988.91   436.0  987.84   466.0  984.15   503.8  982.84   623.8  974.77
   691.6  975.97   703.0  975.87   727.4  974.40   734.9  974.02   742.4  975.66
   751.0  977.55   764.6  982.06   802.7  989.99   830.4  996.69   874.7 1003.41
  1026.2 1033.86  1066.9 1047.22  1164.1 1081.92  1184.1 1090.01  1222.1 1102.86
#Mann= 3 , 0 , 0
       0     0.1       0   727.4   0.045       0   742.4     0.1       0
Bank Sta=   727.4,   742.4
Exp/Cntr=0.3,0.1

Type RM Length L Ch R = 1 ,13231.3,484.366,501.011,514.894
XS GIS Cut Line= 3
     1719744.270      324015.648     1719588.226      323400.779
     1719315.020      322560.563
#Sta/Elev= 30
       0 1080.27    47.2 1064.25   147.9 1047.61   235.3 1029.55   328.2 1014.27
   408.2  998.46   432.6  992.66   475.9  986.35   512.6  982.18   569.1  979.09
   595.4  976.32   618.0  972.31   630.6  972.00   632.1  971.97   645.6  973.34
   664.3  979.79   846.9  985.61   975.8  996.86  1001.0 1000.41  1020.6 1004.42
  1065.7 1016.27  1084.6 1019.94  1125.8 1030.76  1169.9 1041.08  1233.8 1061.73
  1284.4 1076.69  1311.7 1083.05  1349.5 1089.96  1480.5 1128.31  1517.9 1140.10
#Mann= 3 , 0 , 0
       0     0.1       0   630.6   0.045       0   645.6     0.1       0
Bank Sta=   630.6,   645.6
Exp/Cntr=0.3,0.1

Type RM Length L Ch R = 1 ,12730.3,311.404,311.655,314.401
XS GIS Cut Line= 3
     1719780.647      324015.648     1719977.083      323324.482
     1720158.969      322640.592
#Sta/Elev= 30
       0 1080.77    45.4 1065.44    70.8 1059.70   263.7 1023.58   308.3 1018.61
   333.5 1012.90   368.5 1003.34   389.3  995.90   414.5  990.35   454.0  979.42
   553.6  972.06   691.8  971.95   703.3  971.96   714.1  971.97   718.3  973.51
   738.7  980.80   765.5  982.81   829.5 1003.43   913.2 1025.68  1050.0 1058.40
  1088.2 1066.05  1140.0 1075.13  1196.6 1083.01  1241.1 1088.07  1299.1 1090.36
  1329.9 1093.63  1351.9 1097.13  1385.4 1099.53  1414.4 1100.38  1426.2 1103.32
#Mann= 3 , 0 , 0
       0     0.1       0   703.3   0.045       0   718.3     0.1       0
Bank Sta=   703.3,   718.3
Exp/Cntr=0.3,0.1

Type RM Length L Ch R = 1 ,12418.6,459.359,457.169,451.712
XS GIS Cut Line= 3
     1719909.344      324005.162     1720126.044      323534.126
     1720384.507      322924.334
#Sta/Elev= 30
       0 1072.26    19.6 1065.01    37.7 1060.44   108.7 1043.69   160.5 1032.12
   177.1 1029.17   201.0 1026.33   244.5 1019.95   278.6 1016.18   308.2 1011.33
   326.3 1007.99   386.8  994.55   417.8  990.62   444.0  985.74   469.9  977.80
   496.4  972.24     511  972.14     526  972.03   535.2  971.97   614.9  974.33
   664.0  977.21   686.5  979.12   767.3  997.96   826.2 1010.48   847.5 1017.20
   934.1 1052.64   996.5 1071.99  1081.2 1107.20  1093.5 1111.07  1180.8 1130.68
#Mann= 3 , 0 , 0
       0     0.1       0     511   0.045       0     526     0.1       0
Bank Sta=     511,     526
Exp/Cntr=0.3,0.1

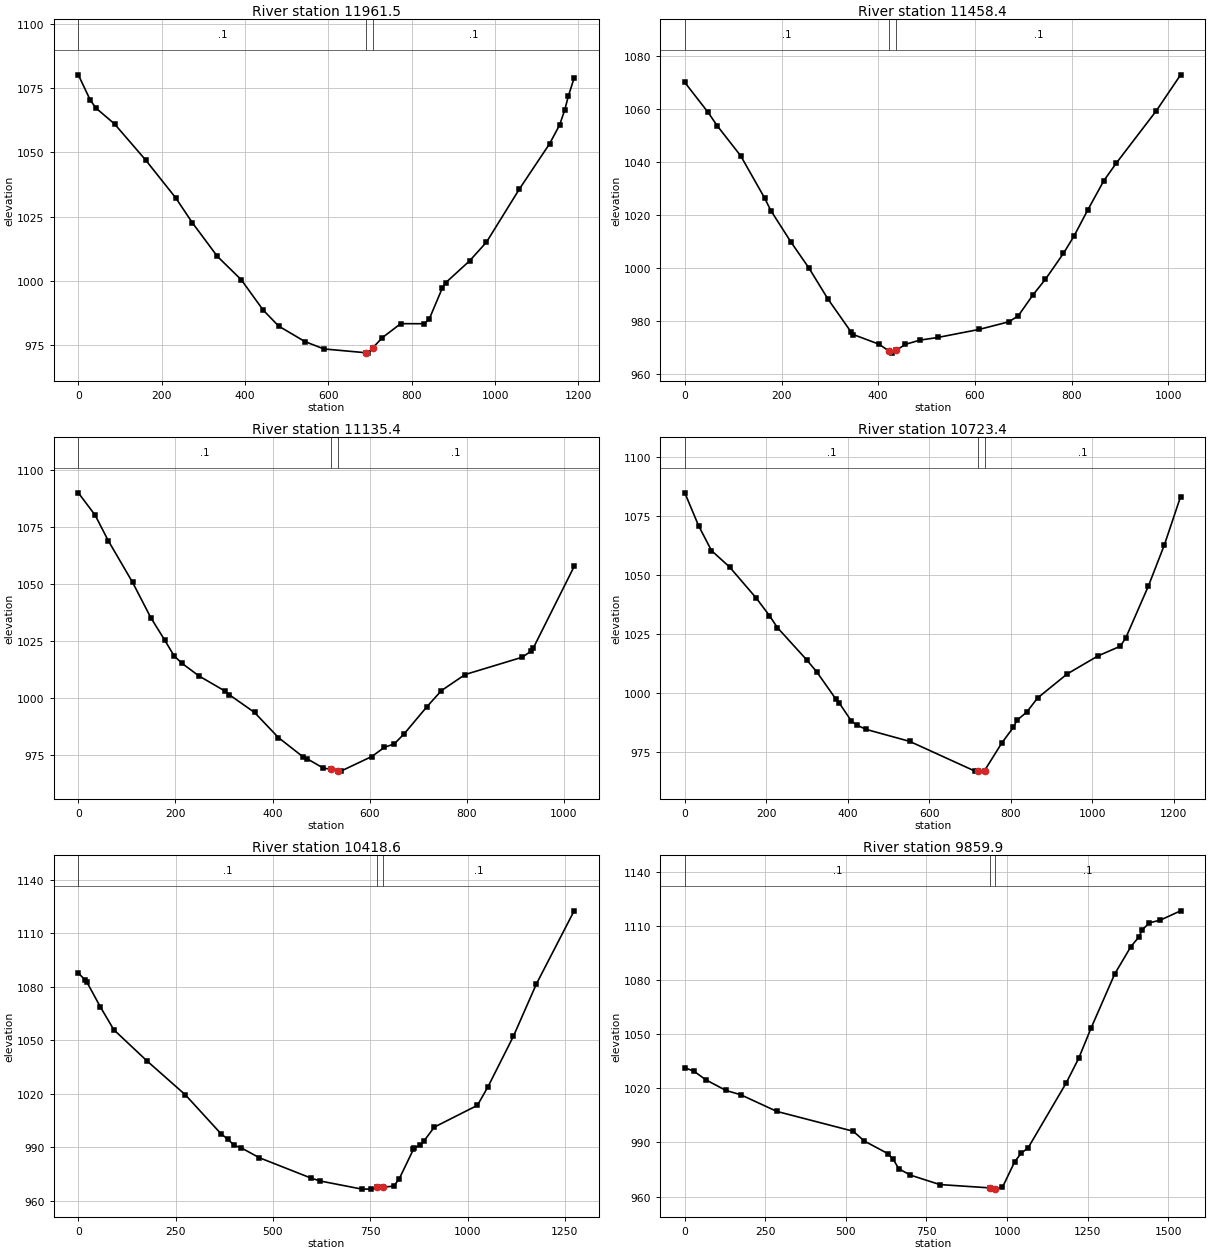
Type RM Length L Ch R = 1 ,11961.5,502.078,503.096,506.96
XS GIS Cut Line= 3
     1720224.448      324255.737     1720464.537      323608.224
     1720550.184      323116.322
#Sta/Elev= 30
       0 1080.16    28.1 1070.50    41.7 1067.31    87.0 1061.03   161.2 1047.07
   233.6 1032.31   273.3 1022.67   333.7 1009.50   391.1 1000.40   443.4  988.65
   480.7  982.39   544.0  976.34   589.4  973.49   691.2  971.99   695.1  971.86
   706.2  973.86   729.7  977.90   773.7  983.33   829.6  983.30   841.7  984.95
   873.4  997.15   882.1  999.33   939.0 1007.77   979.5 1015.05  1058.6 1035.76
  1130.9 1053.32  1155.0 1060.65  1167.1 1066.39  1175.9 1071.84  1189.9 1078.96
#Mann= 3 , 0 , 0
       0     0.1       0   691.2   0.045       0   706.2     0.1       0
Bank Sta=   691.2,   706.2
Exp/Cntr=0.3,0.1

Type RM Length L Ch R = 1 ,11458.4,322.739,322.984,320.261
XS GIS Cut Line= 3
     1720740.377      324266.208     1720896.209      323777.874
     1721027.208      323282.191
#Sta/Elev= 30
       0 1069.94    48.4 1058.59    67.3 1053.51   115.5 1042.26   165.0 1026.32
   177.9 1021.57   219.9 1009.58   256.9  999.82   295.8  988.23   344.5  975.56
   348.4  974.76   402.2  971.08     422  968.53   428.0  967.75     437  968.76
   456.1  971.07   486.2  972.65   522.8  973.65   608.7  976.70   670.0  979.57
   689.5  981.82   719.7  989.66   745.8  995.65   783.0 1005.40   805.0 1011.98
   832.9 1021.67   866.6 1032.87   892.4 1039.51   975.3 1059.30  1025.3 1072.81
#Mann= 3 , 0 , 0
       0     0.1       0     422   0.045       0     437     0.1       0
Bank Sta=     422,     437
Exp/Cntr=0.3,0.1

Type RM Length L Ch R = 1 ,11135.4,422.203,412.024,405.771
XS GIS Cut Line= 3
     1720993.226      324395.669     1721170.253      323913.792
     1721242.712      323411.399
#Sta/Elev= 30
       0 1089.90    34.5 1080.15    61.7 1068.90   111.7 1050.66   149.3 1035.15
   177.6 1025.43   197.3 1018.41   213.3 1015.19   248.3 1009.65   302.9 1002.89
   310.6 1001.44   362.8  993.63   411.9  982.64   463.2  974.08   470.6  973.40
   504.2  969.27   520.3  968.70   535.3  968.12   540.7  967.91   604.3  974.32
   630.3  978.33   650.6  979.86   671.4  984.36   717.9  996.17   747.8 1003.23
   796.4 1010.24   914.0 1017.83   931.3 1020.35   936.5 1021.71  1021.0 1057.62
#Mann= 3 , 0 , 0
       0     0.1       0   520.3   0.045       0   535.3     0.1       0
Bank Sta=   520.3,   535.3
Exp/Cntr=0.3,0.1

Type RM Length L Ch R = 1 ,10723.4,306.228,304.727,299.023
XS GIS Cut Line= 3
     1721701.359      324561.305     1721568.833      323857.591
     1721519.788      323359.633
#Sta/Elev= 30
       0 1084.68    34.0 1070.69    65.5 1060.21   109.8 1053.28   175.2 1040.13
   207.8 1032.64   227.3 1027.57   299.1 1013.94   323.9 1008.81   370.7  997.32
   378.7  995.73   408.5  988.08   423.6  986.19   444.8  984.50   551.7  979.42
   711.9  966.82   720.5  966.86   735.5  967.06   778.1  978.83   806.1  985.36
   814.7  988.31   838.9  991.82   865.7  997.82   938.2 1007.98  1013.8 1015.62
  1068.5 1019.71  1081.9 1023.23  1137.6 1045.28  1176.9 1062.76  1216.5 1083.12
#Mann= 3 , 0 , 0
       0     0.1       0   720.5   0.045       0   735.5     0.1       0
Bank Sta=   720.5,   735.5
Exp/Cntr=0.3,0.1

Type RM Length L Ch R = 1 ,10418.6,569.09,558.705,550.357
XS GIS Cut Line= 3
     1722006.927      324488.550     1721847.463      323729.123
     1721676.675      323261.473
#Sta/Elev= 30
       0 1087.69    17.8 1083.86    22.4 1082.48    56.8 1068.67    91.1 1055.93
   175.2 1038.65   275.2 1019.32   366.9  997.41   383.7  994.54   400.5  990.98
   418.7  989.57   465.1  984.05   598.5  972.56   621.3  970.99   728.7  966.42
   751.2  966.47   768.5  967.39   783.5  967.58   810.4  968.08   824.5  972.26
   860.9  988.79   863.6  989.46   878.5  991.20   887.0  993.19   914.6 1001.25
  1025.3 1013.48  1052.3 1023.86  1117.6 1052.20  1176.9 1081.68  1273.8 1122.70
#Mann= 3 , 0 , 0
       0     0.1       0   768.5   0.045       0   783.5     0.1       0
Bank Sta=   768.5,   783.5
Exp/Cntr=0.3,0.1

Type RM Length L Ch R = 1 ,9859.9,165.321,165.252,166.243
XS GIS Cut Line= 3
     1722923.631      324270.288     1722319.770      323528.194
     1721926.897      323098.944
#Sta/Elev= 30
       0 1031.42    29.5 1029.33    64.8 1024.74   128.0 1018.79   173.0 1016.47
   285.8 1007.19   522.4  996.23   557.4  990.77   630.3  983.81   647.0  980.58
   664.3  975.41   700.3  971.92   791.3  966.70   947.3  964.85   962.3  964.24
   964.1  964.17   985.7  965.17  1023.6  979.30  1044.2  984.14  1065.2  986.97
  1183.7 1023.01  1222.4 1036.63  1260.9 1053.42  1334.2 1083.34  1384.4 1098.49
  1408.0 1103.53  1420.2 1107.86  1441.6 1111.59  1475.9 1113.14  1538.6 1118.26
#Mann= 3 , 0 , 0
       0     0.1       0   947.3   0.045       0   962.3     0.1       0
Bank Sta=   947.3,   962.3
Exp/Cntr=0.3,0.1

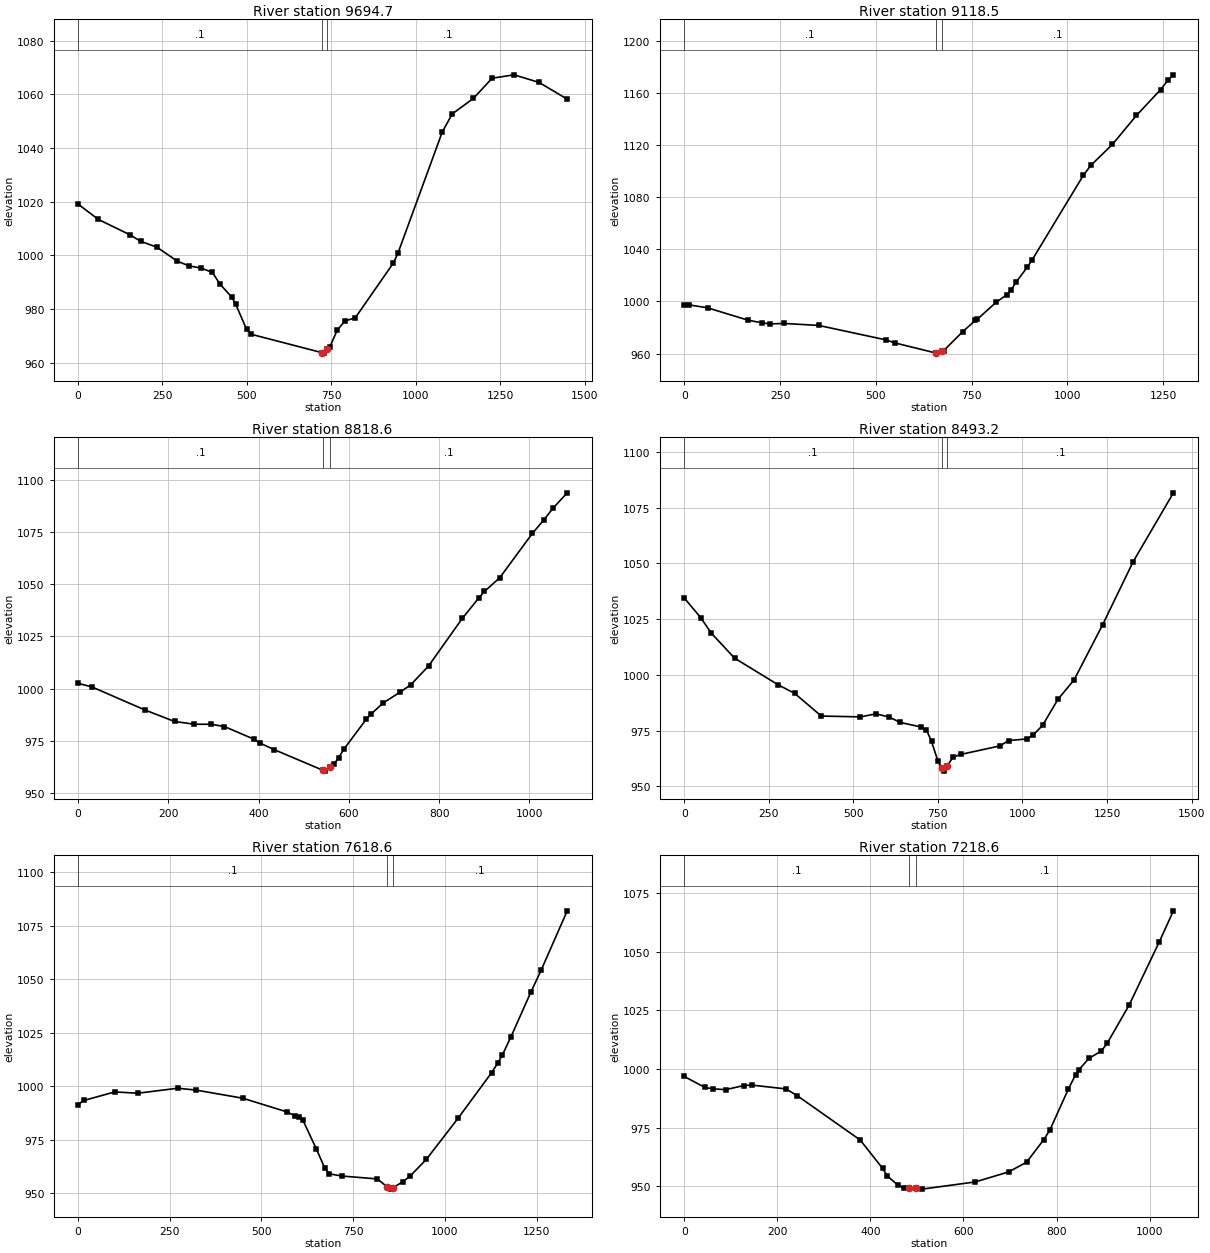
Type RM Length L Ch R = 1 ,9694.7,570.052,576.188,584.04
XS GIS Cut Line= 3
     1722923.631      324015.648     1722458.003      323440.889
     1722006.927      322895.232
#Sta/Elev= 30
       0 1019.11    59.9 1013.39   154.1 1007.62   185.4 1005.21   233.5 1003.02
   293.6  997.84   327.8  996.07   364.5  995.22   397.9  993.61   419.2  989.39
   454.7  984.43   466.3  981.85   498.9  972.37   513.4  970.52   723.1  963.66
   727.9  963.52   738.1  964.96   745.2  965.83   767.2  972.11   790.0  975.49
   820.7  976.72   933.6  997.19   947.1 1000.90  1077.9 1045.97  1107.4 1052.71
  1170.2 1058.52  1225.5 1066.02  1290.4 1067.29  1364.3 1064.46  1447.7 1058.22
#Mann= 3 , 0 , 0
       0     0.1       0   723.1   0.045       0   738.1     0.1       0
Bank Sta=   723.1,   738.1
Exp/Cntr=0.3,0.1

Type RM Length L Ch R = 1 ,9118.5,295.619,299.855,304.349
XS GIS Cut Line= 3
     1723059.091      323605.162     1722770.847      323011.639
     1722567.135      322429.605
#Sta/Elev= 30
       0  997.31    11.5  997.43    61.1  995.10   166.5  985.62   203.4  983.55
   225.0  982.76   260.0  983.10   351.0  981.58   526.6  970.46   550.0  968.12
   656.6  960.40   658.1  960.30   671.6  961.57   676.6  962.11   726.3  976.66
   759.3  985.37   765.1  986.41   813.6  999.27   842.3 1005.27   852.1 1008.42
   866.1 1014.90   895.4 1026.39   907.6 1031.82  1041.5 1096.91  1061.8 1104.79
  1117.2 1120.63  1180.1 1142.94  1242.8 1162.68  1262.6 1170.07  1276.5 1174.13
#Mann= 3 , 0 , 0
       0     0.1       0   656.6   0.045       0   671.6     0.1       0
Bank Sta=   656.6,   671.6
Exp/Cntr=0.3,0.1

Type RM Length L Ch R = 1 ,8818.6,326.916,325.44,322.138
XS GIS Cut Line= 3
     1723150.214      323572.121     1723055.127      323030.446
     1722996.819      322499.816
#Sta/Elev= 30
       0 1002.52    30.2 1000.86   149.0  989.71   213.8  984.26   257.4  982.95
   295.3  982.91   324.4  981.83   389.7  975.79   403.3  973.89   435.1  970.73
   542.5  960.90   546.9  960.48   557.5  962.24   567.2  963.81   577.1  966.88
   590.0  971.28   639.1  985.45   650.1  988.00   676.3  993.16   714.4  998.42
   737.4 1001.88   776.5 1010.81   851.2 1033.59   888.7 1043.63   900.4 1046.54
   934.3 1053.10  1006.8 1074.38  1032.5 1080.95  1052.4 1086.42  1083.8 1093.77
#Mann= 3 , 0 , 0
       0     0.1       0   542.5   0.045       0   557.5     0.1       0
Bank Sta=   542.5,   557.5
Exp/Cntr=0.3,0.1

Type RM Length L Ch R = 1 ,8493.2,870.264,874.56,879.592
XS GIS Cut Line= 3
     1723585.694      323841.038     1723360.156      323062.567
     1723095.793      322484.566
#Sta/Elev= 30
       0 1034.46    48.9 1025.61    79.5 1018.76   149.1 1007.43   277.4  995.52
   326.3  991.67   405.3  981.48   521.0  981.11   566.9  982.47   605.5  981.05
   638.9  978.59   701.3  976.55   716.1  975.21   731.1  970.08   750.4  961.13
   762.3  958.14   768.2  956.78   777.3  959.00   794.4  963.04   817.6  964.27
   932.9  968.08   958.8  970.48  1014.6  971.24  1032.0  973.07  1059.3  977.26
  1104.6  988.95  1152.7  997.75  1237.1 1022.50  1327.2 1050.74  1446.1 1081.59
#Mann= 3 , 0 , 0
       0     0.1       0   762.3   0.045       0   777.3     0.1       0
Bank Sta=   762.3,   777.3
Exp/Cntr=0.3,0.1

Type RM Length L Ch R = 1 ,7618.6,404.506,400,396.736
XS GIS Cut Line= 3
     1723993.118      323462.715     1723895.196      322618.667
     1723855.202      322136.608
#Sta/Elev= 30
       0  991.49    15.8  993.39   100.4  997.37   163.2  996.77   271.9  999.10
   322.1  998.22   449.3  994.43   570.9  987.97   592.4  986.12   601.9  985.73
   612.9  984.23   649.7  970.73   672.7  961.80   684.7  959.16   720.0  958.12
   816.1  956.77   842.2  953.11   852.0  952.02   857.2  952.56   885.1  955.42
   906.1  958.28   949.2  965.87  1035.5  985.00  1127.6 1006.42  1143.4 1010.65
  1156.0 1014.38  1180.4 1023.23  1234.1 1043.87  1262.3 1054.19  1333.4 1081.87
#Mann= 3 , 0 , 0
       0     0.1       0   842.2   0.045       0   857.2     0.1       0
Bank Sta=   842.2,   857.2
Exp/Cntr=0.3,0.1

Type RM Length L Ch R = 1 ,7218.6,390.09,400,400.131
XS GIS Cut Line= 3
     1724404.001      323133.845     1724256.956      322665.012
     1724136.392      322118.421
#Sta/Elev= 30
       0  996.85    44.6  992.13    62.8  991.53    89.2  991.21   128.2  992.96
   144.8  993.15   218.8  991.52   243.2  988.59   378.0  969.77   426.1  957.73
   436.0  954.50   459.9  950.40   472.1  949.44   483.9  949.49   498.9  949.25
   510.7  948.82   625.5  951.89   697.1  956.16   735.7  960.31   772.1  969.78
   785.5  973.93   825.3  991.41   840.9  997.56   847.7  999.57   869.4 1004.50
   896.4 1007.70   909.2 1011.08   955.6 1027.11  1020.3 1054.00  1051.1 1067.40
#Mann= 3 , 0 , 0
       0     0.1       0   483.9   0.045       0   498.9     0.1       0
Bank Sta=   483.9,   498.9
Exp/Cntr=0.3,0.1

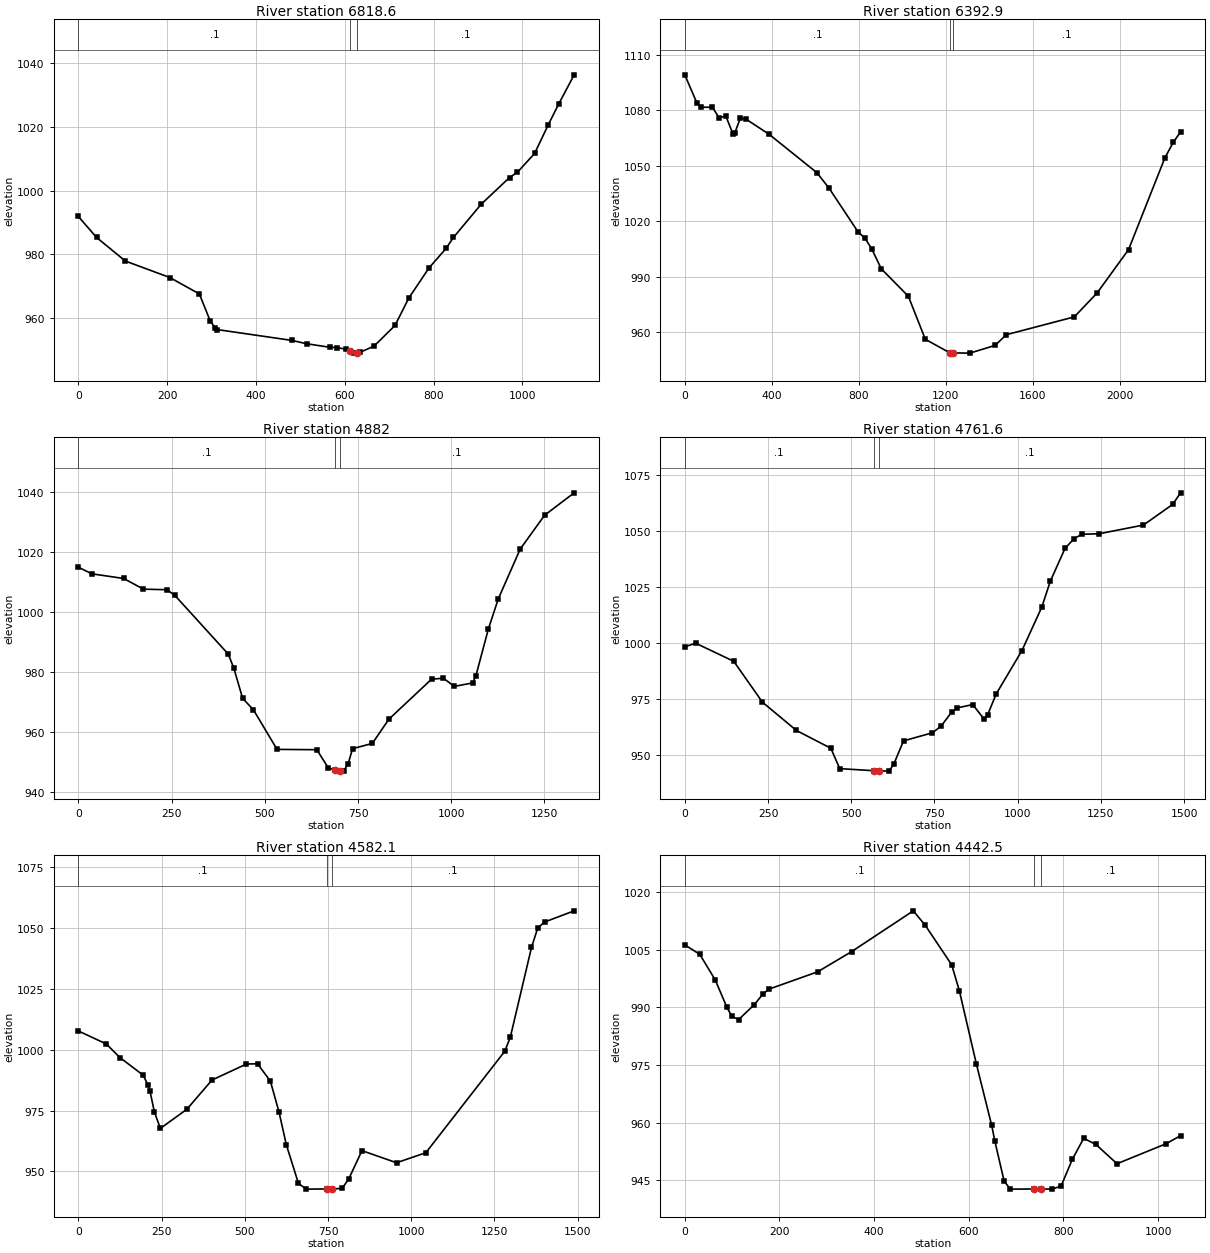
Type RM Length L Ch R = 1 ,6818.6,438.275,425.718,420.961
XS GIS Cut Line= 3
     1724505.089      323111.880     1724592.410      322497.824
     1724528.693      322005.628
#Sta/Elev= 30
       0  991.86    41.1  985.26   106.0  977.84   206.0  972.67   272.6  967.50
   296.6  959.12   308.6  956.70   312.8  956.30   481.8  952.88   513.9  951.85
   565.6  950.76   582.5  950.65   602.8  950.11   612.7  949.45   621.2  948.90
   627.7  949.01   633.6  949.11   665.9  951.10   713.1  957.60   744.1  966.20
   789.8  975.71   828.0  981.81   844.8  985.29   907.2  995.72   971.0 1004.11
   988.4 1005.71  1027.4 1011.66  1057.8 1020.57  1082.1 1027.34  1116.5 1036.39
#Mann= 3 , 0 , 0
       0     0.1       0   612.7   0.045       0   627.7     0.1       0
Bank Sta=   612.7,   627.7
Exp/Cntr=0.3,0.1

Type RM Length L Ch R = 1 ,6392.9,1538.703,1510.878,1483.136
XS GIS Cut Line= 3
     1724938.923      324001.097     1724902.546      322444.156
     1724553.326      321811.194
#Sta/Elev= 30
       0 1099.06    55.3 1083.96    74.7 1081.59   127.0 1081.53   157.0 1076.00
   189.3 1076.70   221.2 1067.18   230.5 1067.77   255.0 1075.64   280.6 1075.19
   386.2 1067.09   607.4 1046.25   663.9 1037.78   796.1 1014.39   828.5 1010.86
   859.1 1005.27   903.5  994.35  1028.2  979.49  1106.1  956.30  1219.6  948.93
  1234.6  948.94  1310.9  948.82  1427.0  952.98  1479.0  958.78  1791.4  968.38
  1896.7  981.37  2040.8 1004.70  2207.7 1054.17  2247.0 1062.75  2280.3 1068.28
#Mann= 3 , 0 , 0
       0     0.1       0  1219.6   0.045       0  1234.6     0.1       0
Bank Sta=  1219.6,  1234.6
Exp/Cntr=0.3,0.1

Type RM Length L Ch R = 1 ,4882,115.318,120.437,125.471
XS GIS Cut Line= 4
     1725881.268      321774.032     1725331.751      321613.301
     1724859.010      321630.573     1724611.877      321490.633
#Sta/Elev= 30
       0 1014.97    36.5 1012.76   121.7 1011.20   174.6 1007.64   237.6 1007.45
   258.8 1005.56   402.0  985.95   416.8  981.32   440.6  971.18   469.5  967.35
   532.9  954.13   639.6  954.02   670.1  947.99     687  947.32     702  946.94
   711.3  946.87   723.4  949.29   735.4  954.37   788.4  956.12   832.7  964.20
   947.2  977.57   979.0  977.90  1008.2  975.17  1057.4  976.32  1066.2  978.75
  1099.7  994.41  1126.1 1004.39  1184.9 1021.02  1250.4 1032.33  1329.6 1039.81
#Mann= 3 , 0 , 0
       0     0.1       0     687   0.045       0     702     0.1       0
Bank Sta=     687,     702
Exp/Cntr=0.3,0.1

Type RM Length L Ch R = 1 ,4761.6,180.957,179.539,178.121
XS GIS Cut Line= 3
     1725827.322      321601.890     1725207.615      321499.768
     1724349.747      321420.302
#Sta/Elev= 30
       0  998.26    32.8  999.83   147.0  991.76   233.2  973.49   335.3  960.83
   438.8  952.86   465.4  943.77     567  942.84     582  942.79   613.5  942.65
   628.0  945.82   657.1  956.17   743.8  959.79   769.4  962.66   802.2  969.11
   819.1  970.93   864.9  972.41   899.4  965.88   909.9  967.86   935.6  977.18
  1012.9  996.55  1072.3 1015.90  1098.3 1027.61  1142.5 1042.29  1169.5 1046.55
  1192.4 1048.52  1245.7 1048.80  1377.8 1052.66  1465.5 1061.88  1489.6 1067.07
#Mann= 3 , 0 , 0
       0     0.1       0     567   0.045       0     582     0.1       0
Bank Sta=     567,     582
Exp/Cntr=0.3,0.1

Type RM Length L Ch R = 1 ,4582.1,139.291,139.57,140.136
XS GIS Cut Line= 3
     1726053.323      321451.340     1725433.616      321349.218
     1724575.748      321269.752
#Sta/Elev= 30
       0 1007.77    84.1 1002.41   124.8  996.83   194.8  989.59   209.6  985.43
   215.5  982.88   228.5  974.43   246.5  967.69   326.0  975.55   401.4  987.56
   504.7  994.15   538.3  994.28   577.0  987.12   603.0  974.36   624.8  961.01
   661.3  945.06   685.2  942.72   747.6  942.80   762.6  942.86   792.5  942.98
   812.8  947.04   852.1  958.54   956.1  953.57  1044.1  957.70  1281.4  999.46
  1297.9 1005.25  1361.4 1042.09  1380.2 1050.10  1400.6 1052.55  1489.6 1057.16
#Mann= 3 , 0 , 0
       0     0.1       0   747.6   0.045       0   762.6     0.1       0
Bank Sta=   747.6,   762.6
Exp/Cntr=0.3,0.1

Type RM Length L Ch R = 1 ,4442.5,251.276,256.623,261.308
XS GIS Cut Line= 4
     1726043.972      321311.070     1725424.265      321208.948
     1725189.193      321187.173     1725019.968      321257.681
#Sta/Elev= 30
       0 1006.23    31.7 1003.75    64.2  997.12    88.7  990.06    99.2  987.63
   113.7  986.79   146.8  990.66   165.7  993.54   178.3  994.73   280.4  999.20
   352.2 1004.45   482.8 1015.08   507.8 1011.33   563.9 1001.03   580.0  994.30
   616.1  975.19   648.4  959.25   654.9  955.23   674.7  944.73   687.9  942.68
   737.6  942.71   752.6  942.70   776.7  942.70   795.0  943.49   818.6  950.39
   842.7  955.90   868.3  954.32   913.1  949.29  1016.1  954.45  1047.5  956.59
#Mann= 3 , 0 , 0
       0     0.1       0   737.6   0.045       0   752.6     0.1       0
Bank Sta=   737.6,   752.6
Exp/Cntr=0.3,0.1