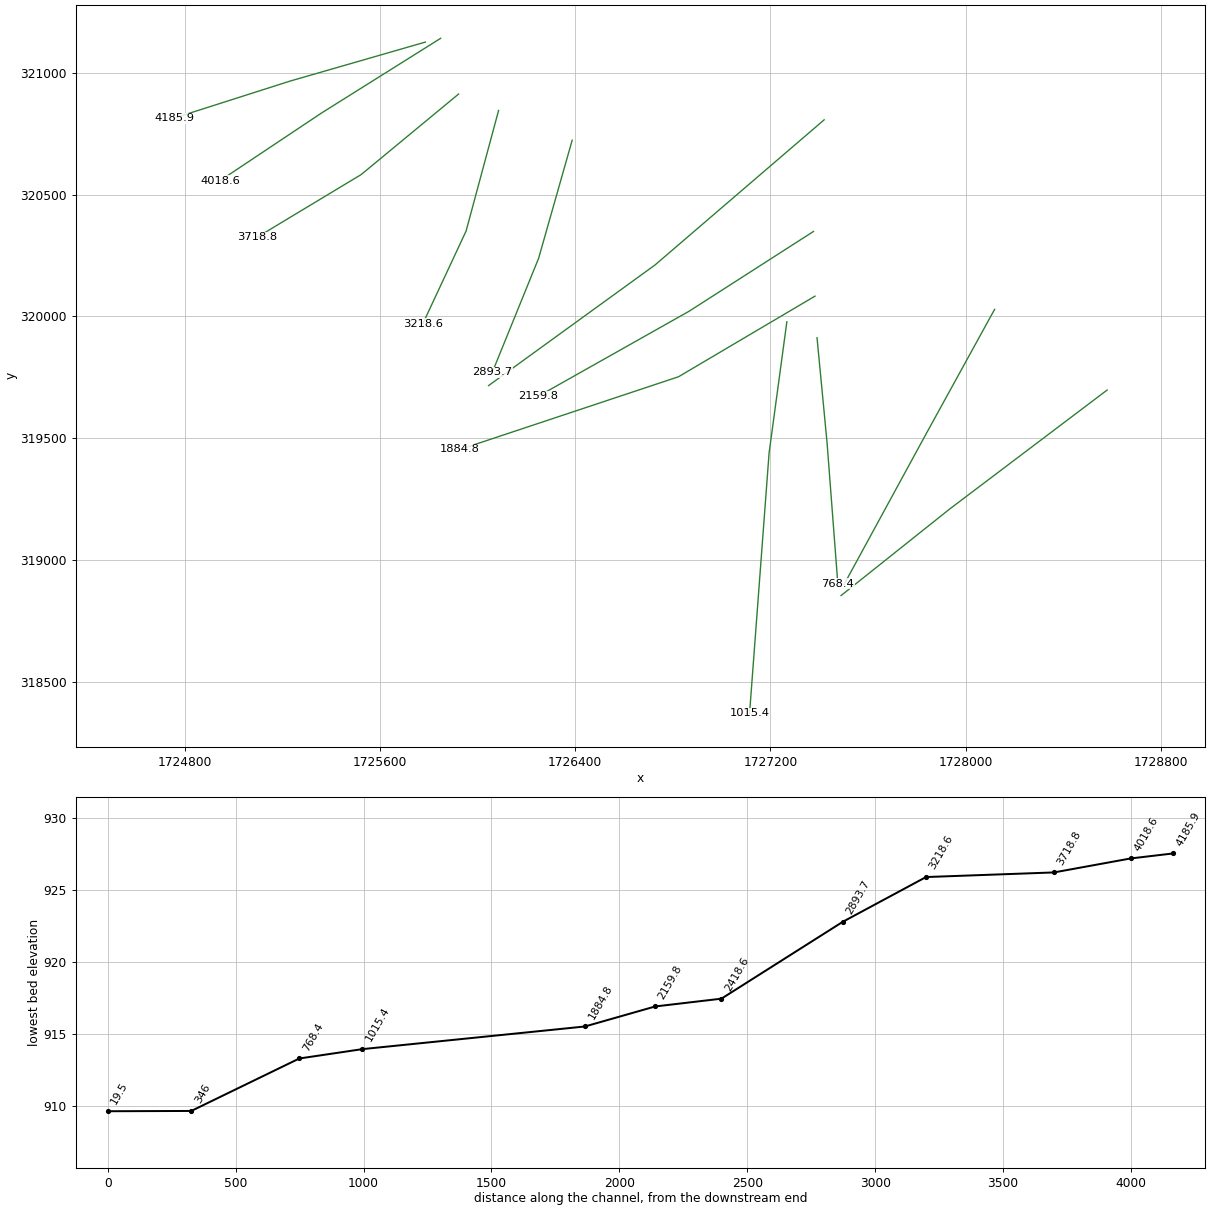
HEC-RAS study JonesCr.prj: JonesCr

--- JonesCr.g01 (geometry) --- (continued)

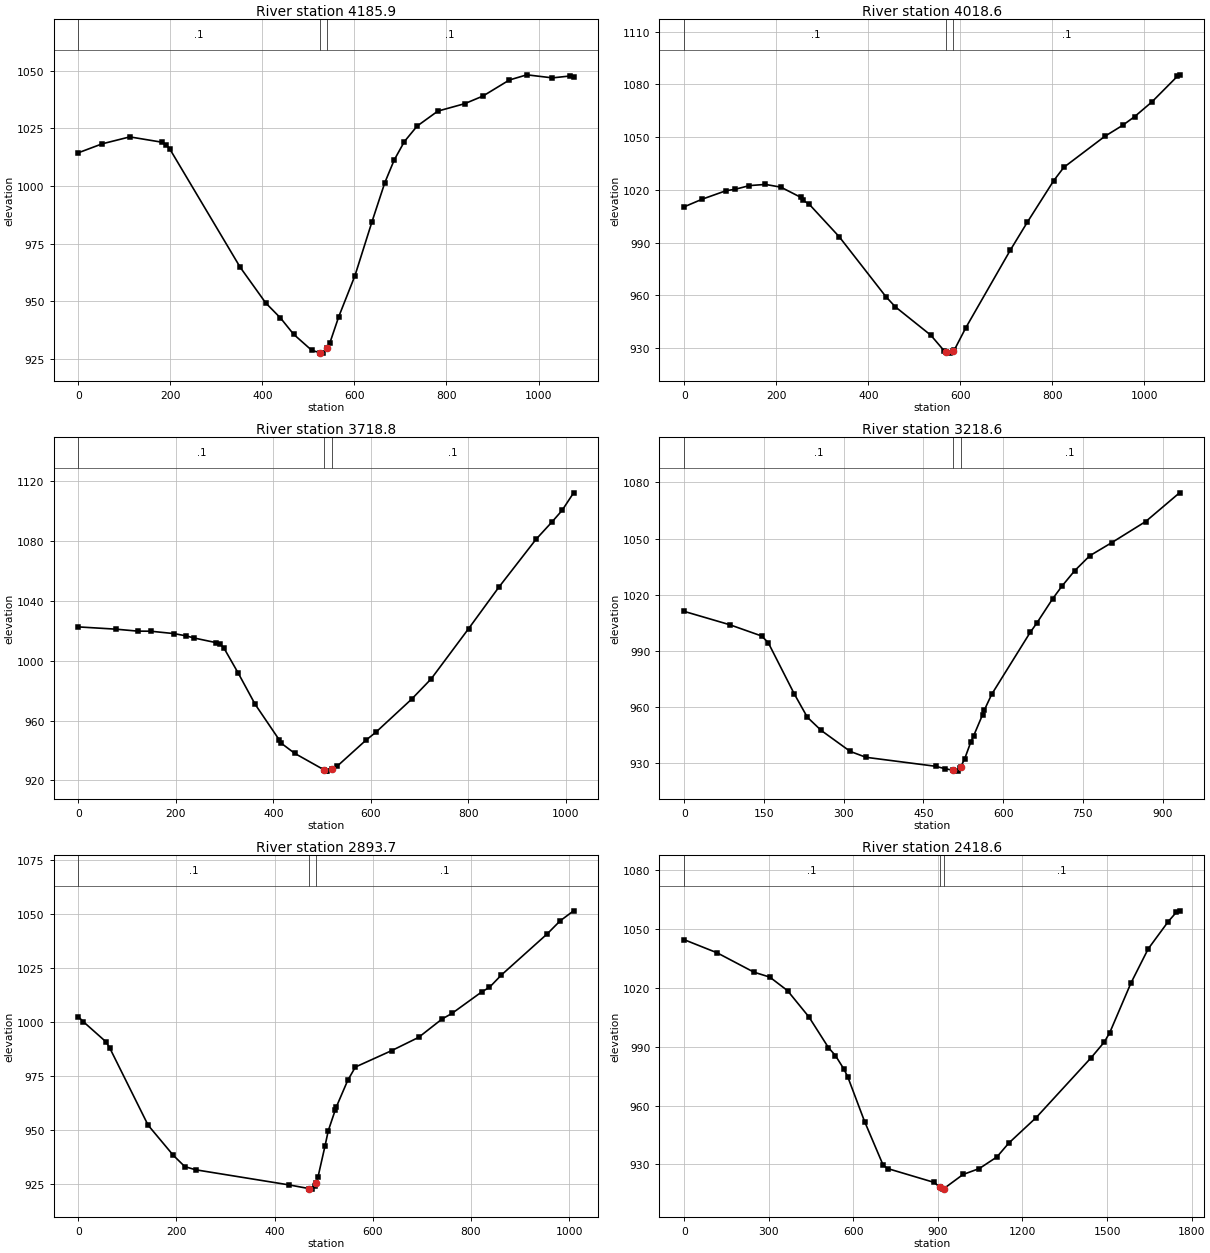
Type RM Length L Ch R = 1 ,4185.9,160.85,167.237,174.469
XS GIS Cut Line= 3
     1725785.908      321126.497     1725231.367      320966.266
     1724756.079      320814.239
#Sta/Elev= 30
       0 1014.36    51.9 1018.25   111.9 1021.25   181.9 1018.94   191.1 1017.66
   198.3 1016.17   351.8  964.72   407.2  949.29   439.3  942.76   467.8  935.71
   507.3  928.73   524.5  927.73   531.5  927.53   539.5  929.61   546.3  931.78
   565.8  943.29   601.1  961.11   637.9  984.35   666.0 1001.42   686.4 1011.25
   708.6 1019.25   736.2 1025.94   781.2 1032.43   839.5 1035.64   879.2 1038.95
   936.7 1045.92   974.6 1048.15  1030.2 1046.83  1069.0 1047.66  1076.2 1047.30
#Mann= 3 , 0 , 0
       0     0.1       0   524.5   0.045       0   539.5     0.1       0
Bank Sta=   524.5,   539.5
Exp/Cntr=0.3,0.1

Type RM Length L Ch R = 1 ,4018.6,296.922,299.872,299.733
XS GIS Cut Line= 3
     1725848.352      321141.855     1725359.582      320834.782
     1724944.722      320557.469
#Sta/Elev= 30
       0 1010.41    39.3 1014.77    91.1 1019.59   110.9 1020.38   141.7 1022.48
   176.5 1023.14   210.0 1021.59   252.9 1015.85   258.2 1014.10   271.5 1011.90
   336.7  993.41   438.2  959.31   458.8  953.50   535.8  937.38   564.3  928.67
   569.7  927.99   577.2  927.18   584.7  928.56   586.8  928.92   611.8  941.58
   708.2  985.59   745.6 1001.68   802.9 1025.30   824.8 1032.85   913.6 1050.44
   952.4 1056.71   978.8 1061.73  1016.0 1070.02  1071.2 1084.56  1076.2 1085.48
#Mann= 3 , 0 , 0
       0     0.1       0   569.7   0.045       0   584.7     0.1       0
Bank Sta=   569.7,   584.7
Exp/Cntr=0.3,0.1

Type RM Length L Ch R = 1 ,3718.8,486.105,500.128,512.354
XS GIS Cut Line= 3
     1725921.975      320913.120     1725522.797      320582.445
     1725096.987      320325.459
#Sta/Elev= 30
       0 1022.63    76.9 1021.12   122.2 1019.79   148.3 1019.75   196.2 1018.15
   221.3 1016.62   238.0 1015.17   282.2 1012.13   291.0 1011.04   299.0 1008.28
   328.0  991.70   362.5  970.95   412.0  947.14   416.4  944.81   443.6  938.12
   504.8  926.92   508.7  926.21   510.7  926.23   519.8  927.75   531.2  929.61
   589.2  946.70   610.5  952.30   683.6  974.35   723.6  987.89   800.3 1021.43
   862.7 1049.31   938.6 1081.18   971.7 1092.92   991.9 1100.45  1015.7 1112.26
#Mann= 3 , 0 , 0
       0     0.1       0   504.8   0.045       0   519.8     0.1       0
Bank Sta=   504.8,   519.8
Exp/Cntr=0.3,0.1

Type RM Length L Ch R = 1 ,3218.6,325.291,324.969,328.898
XS GIS Cut Line= 3
     1726085.833      320845.582     1725952.660      320350.457
     1725775.597      319970.511
#Sta/Elev= 30
       0 1011.12    85.7 1004.00   145.7  997.99   158.0  994.48   207.1  967.09
   231.7  954.64   257.7  947.61   312.3  936.42   342.0  933.27   472.9  928.48
   490.0  927.23   505.2  926.40   514.6  925.89   518.9  927.40   520.2  928.15
   527.7  932.46   538.9  941.18   544.5  944.69   561.3  955.96   564.8  958.55
   578.6  966.91   651.0  999.93   663.0 1004.72   693.3 1017.88   710.4 1024.48
   734.7 1032.84   763.1 1040.81   804.5 1047.82   868.3 1059.08   931.9 1074.38
#Mann= 3 , 0 , 0
       0     0.1       0   505.2   0.045       0   520.2     0.1       0
Bank Sta=   505.2,   520.2
Exp/Cntr=0.3,0.1

Type RM Length L Ch R = 1 ,2893.7,490.551,475.03,454.536
XS GIS Cut Line= 3
     1726387.396      320723.438     1726249.863      320238.569
     1726060.056      319770.453
#Sta/Elev= 30
       0 1002.62    10.2 1000.30    56.3  991.00    64.4  987.97   142.2  952.39
   193.4  938.47   217.0  933.21   238.9  931.75   429.5  924.74   469.5  923.06
   475.9  922.79   482.3  924.08   484.5  925.64   488.2  928.28   502.5  942.64
   509.2  949.77   523.8  959.63   525.5  960.75   548.9  973.14   564.5  979.31
   638.9  986.96   693.3  993.04   741.1 1001.55   761.1 1004.11   821.6 1014.04
   837.7 1016.21   861.7 1021.86   955.6 1041.01   981.7 1046.99  1009.1 1051.62
#Mann= 3 , 0 , 0
       0     0.1       0   469.5   0.045       0   484.5     0.1       0
Bank Sta=   469.5,   484.5
Exp/Cntr=0.3,0.1

Type RM Length L Ch R = 1 ,2418.6,259.285,258.88,263.45
XS GIS Cut Line= 3
     1727419.843      320807.185     1726726.965      320211.296
     1726044.788      319715.872
#Sta/Elev= 30
       0 1044.51   116.8 1037.83   247.3 1027.97   303.5 1025.47   366.5 1018.56
   442.3 1005.19   511.5  989.58   536.3  985.51   566.6  978.59   580.7  974.44
   639.9  951.89   706.0  929.56   721.6  927.93   887.6  920.83   906.4  918.37
   919.2  917.45   921.4  917.75   989.1  924.91  1046.7  927.92  1109.2  933.84
  1151.3  940.89  1248.7  953.92  1444.1  984.50  1489.9  992.32  1509.6  997.19
  1584.8 1022.46  1645.9 1039.84  1717.1 1053.77  1746.2 1058.57  1757.0 1059.22
#Mann= 3 , 0 , 0
       0     0.1       0   906.4   0.045       0   921.4     0.1       0
Bank Sta=   906.4,   921.4
Exp/Cntr=0.3,0.1

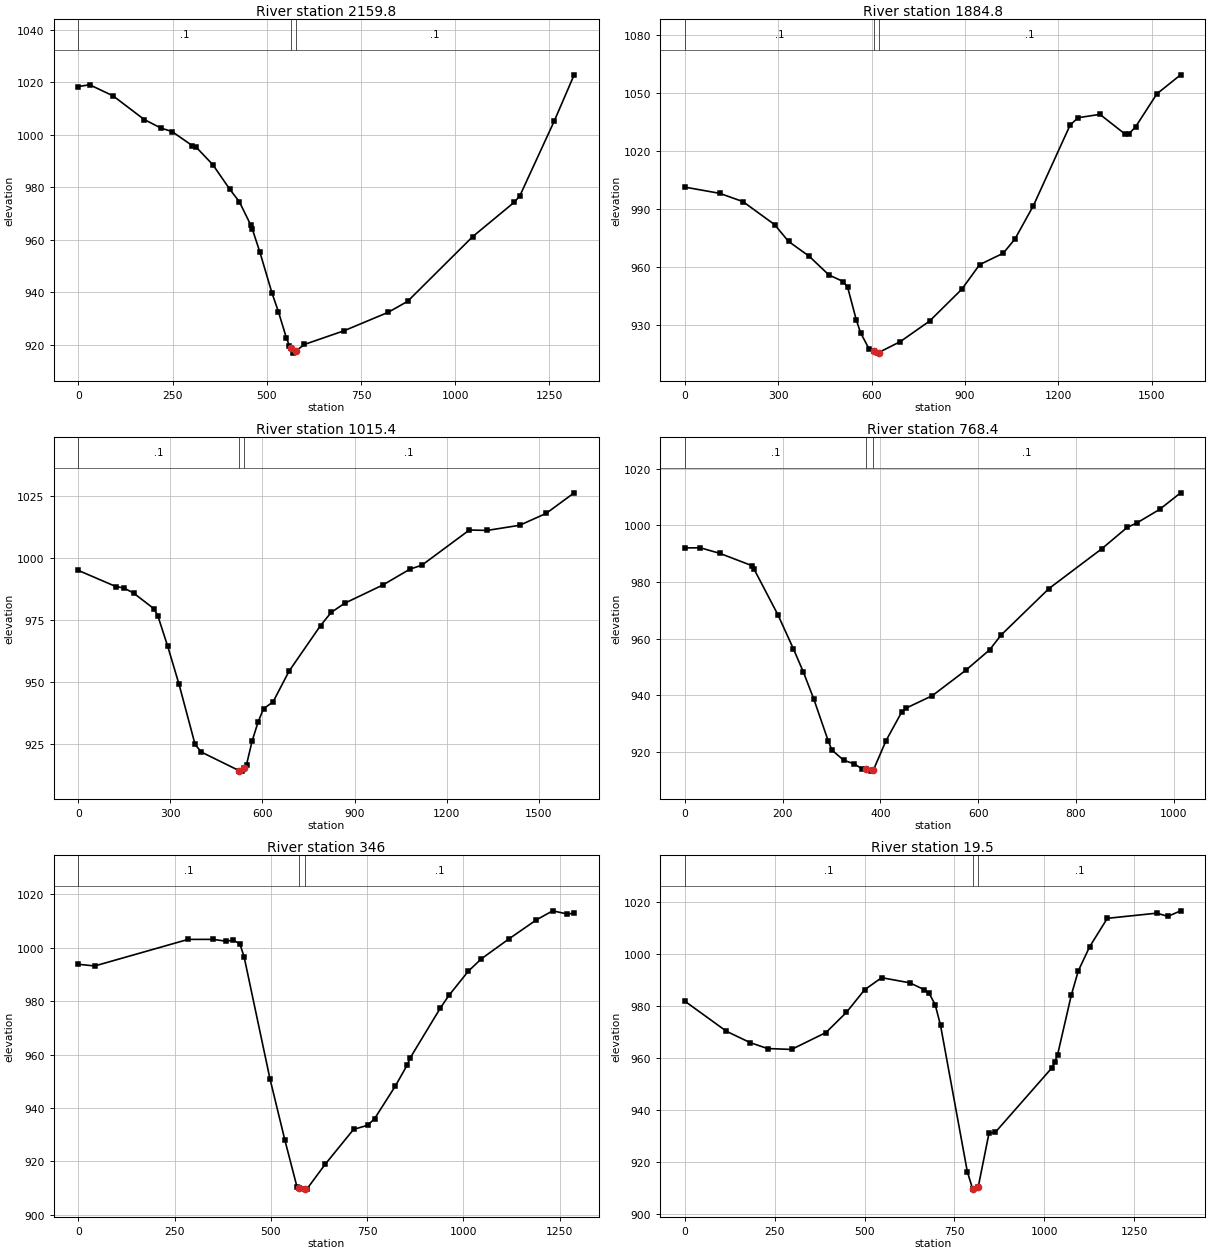
Type RM Length L Ch R = 1 ,2159.8,271.52,274.983,278.447
XS GIS Cut Line= 3
     1727376.191      320348.833     1726866.911      320021.439
     1726248.500      319672.219
#Sta/Elev= 30
       0 1018.38    29.9 1019.06    92.2 1014.83   175.1 1005.80   219.7 1002.55
   248.8 1001.23   302.1  995.92   312.8  995.29   356.9  988.62   402.1  979.23
   427.3  974.50   457.4  965.70   462.0  963.98   481.9  955.26   513.9  939.74
   531.0  932.63   552.2  922.62   559.8  919.79   563.4  918.80   570.3  916.91
   578.4  917.84   599.6  920.20   705.0  925.42   822.2  932.45   873.7  936.62
  1046.6  961.28  1157.0  974.38  1171.4  976.76  1262.4 1005.13  1315.6 1022.84
#Mann= 3 , 0 , 0
       0     0.1       0   563.4   0.045       0   578.4     0.1       0
Bank Sta=   563.4,   578.4
Exp/Cntr=0.3,0.1

Type RM Length L Ch R = 1 ,1884.8,855.595,869.377,883.718
XS GIS Cut Line= 3
     1727382.333      320083.190     1726823.259      319752.249
     1725928.381      319453.956
#Sta/Elev= 30
       0 1001.34   112.1  998.12   186.9  993.84   288.7  981.92   333.2  973.28
   399.1  965.66   463.2  955.90   509.5  952.49   523.3  949.52   550.9  932.71
   564.7  926.07   592.2  917.62   607.8  916.39   619.4  915.52   622.8  915.82
   692.3  921.46   786.4  932.09   889.9  948.54   947.2  961.25  1023.1  967.17
  1060.6  974.48  1120.0  991.75  1238.1 1033.45  1263.6 1037.20  1333.7 1038.95
  1413.7 1028.85  1425.8 1028.68  1448.3 1032.50  1516.9 1049.58  1593.0 1059.38
#Mann= 3 , 0 , 0
       0     0.1       0   607.8   0.045       0   622.8     0.1       0
Bank Sta=   607.8,   622.8
Exp/Cntr=0.3,0.1

Type RM Length L Ch R = 1 ,1015.4,239.721,246.98,253.679
XS GIS Cut Line= 3
     1727267.060      319977.787     1727194.305      319439.405
     1727114.276      318369.918
#Sta/Elev= 30
       0  994.97   122.4  988.46   147.8  987.90   179.9  985.84   246.0  979.53
   258.9  976.72   291.3  964.31   328.2  948.99   380.5  924.70   400.8  921.65
   524.3  914.12   533.9  913.95   539.3  915.03   548.2  916.61   566.4  926.12
   586.0  933.87   603.5  939.11   634.6  941.91   686.7  954.30   789.2  972.70
   823.9  978.00   867.5  981.68   992.4  989.09  1080.9  995.50  1119.6  997.08
  1274.4 1011.28  1332.5 1011.12  1438.2 1013.19  1524.6 1017.99  1615.8 1026.29
#Mann= 3 , 0 , 0
       0     0.1       0   524.3   0.045       0   539.3     0.1       0
Bank Sta=   524.3,   539.3
Exp/Cntr=0.3,0.1

Type RM Length L Ch R = 1 ,768.4,435.742,422.401,409.152
XS GIS Cut Line= 3
     1727390.742      319912.308     1727431.955      319479.830
     1727476.006      318901.656
#Sta/Elev= 30
       0  992.04    31.8  992.08    71.6  990.12   136.6  985.83   141.4  984.64
   190.3  968.51   222.0  956.51   242.8  948.15   263.7  938.81   293.3  924.01
   301.0  920.72   324.9  917.16   345.6  915.91   362.8  914.13     371  913.95
   380.7  913.30     386  913.77   411.6  924.03   444.1  934.25   453.3  935.57
   506.3  939.91   575.1  948.92   623.7  956.10   646.6  961.23   745.1  977.72
   852.9  991.72   904.9  999.26   924.8 1000.85   971.3 1005.62  1014.3 1011.47
#Mann= 3 , 0 , 0
       0     0.1       0     371   0.045       0     386     0.1       0
Bank Sta=     371,     386
Exp/Cntr=0.3,0.1

Type RM Length L Ch R = 1 ,346,335.672,326.494,317.923
XS GIS Cut Line= 3
     1728118.284      320028.715     1727839.364      319520.641
     1727501.240      318898.840
#Sta/Elev= 30
       0  993.79    42.4  993.16   285.1 1003.10   349.4 1003.11   384.4 1002.41
   401.9 1002.84   419.4 1001.45   430.4  996.59   497.5  950.98   536.5  927.87
   568.0  910.35     574  910.07     589  909.75   593.2  909.66   641.3  919.02
   714.6  932.00   751.8  933.59   769.3  936.05   822.9  948.18   853.3  955.94
   862.1  958.86   940.1  977.45   962.8  982.25  1012.5  991.19  1046.7  995.86
  1119.3 1003.41  1189.5 1010.42  1231.7 1013.79  1269.9 1012.59  1287.4 1012.88
#Mann= 3 , 0 , 0
       0     0.1       0     574   0.045       0     589     0.1       0
Bank Sta=     574,     589
Exp/Cntr=0.3,0.1

Type RM Length L Ch R = 1 ,19.5,29.682,19.514,8.648
XS GIS Cut Line= 3
     1728579.490      319697.659     1727934.612      319209.365
     1727489.205      318853.711
#Sta/Elev= 30
       0  981.84   115.9  970.27   181.9  965.91   230.1  963.64   296.8  963.30
   392.6  969.79   449.2  977.49   500.1  986.22   547.4  990.86   625.9  988.88
   665.1  986.30   678.8  985.03   696.3  980.50   711.2  972.55   785.7  916.34
   800.6  909.64   801.1  909.65   816.1  910.53   846.0  931.14   863.6  931.48
  1020.5  956.16  1028.3  958.30  1036.5  961.14  1074.8  984.11  1094.3  993.47
  1125.9 1002.75  1175.0 1013.66  1312.6 1015.64  1343.7 1014.42  1378.9 1016.54
#Mann= 3 , 0 , 0
       0     0.1       0   801.1   0.045       0   816.1     0.1       0
Bank Sta=   801.1,   816.1
Exp/Cntr=0.3,0.1